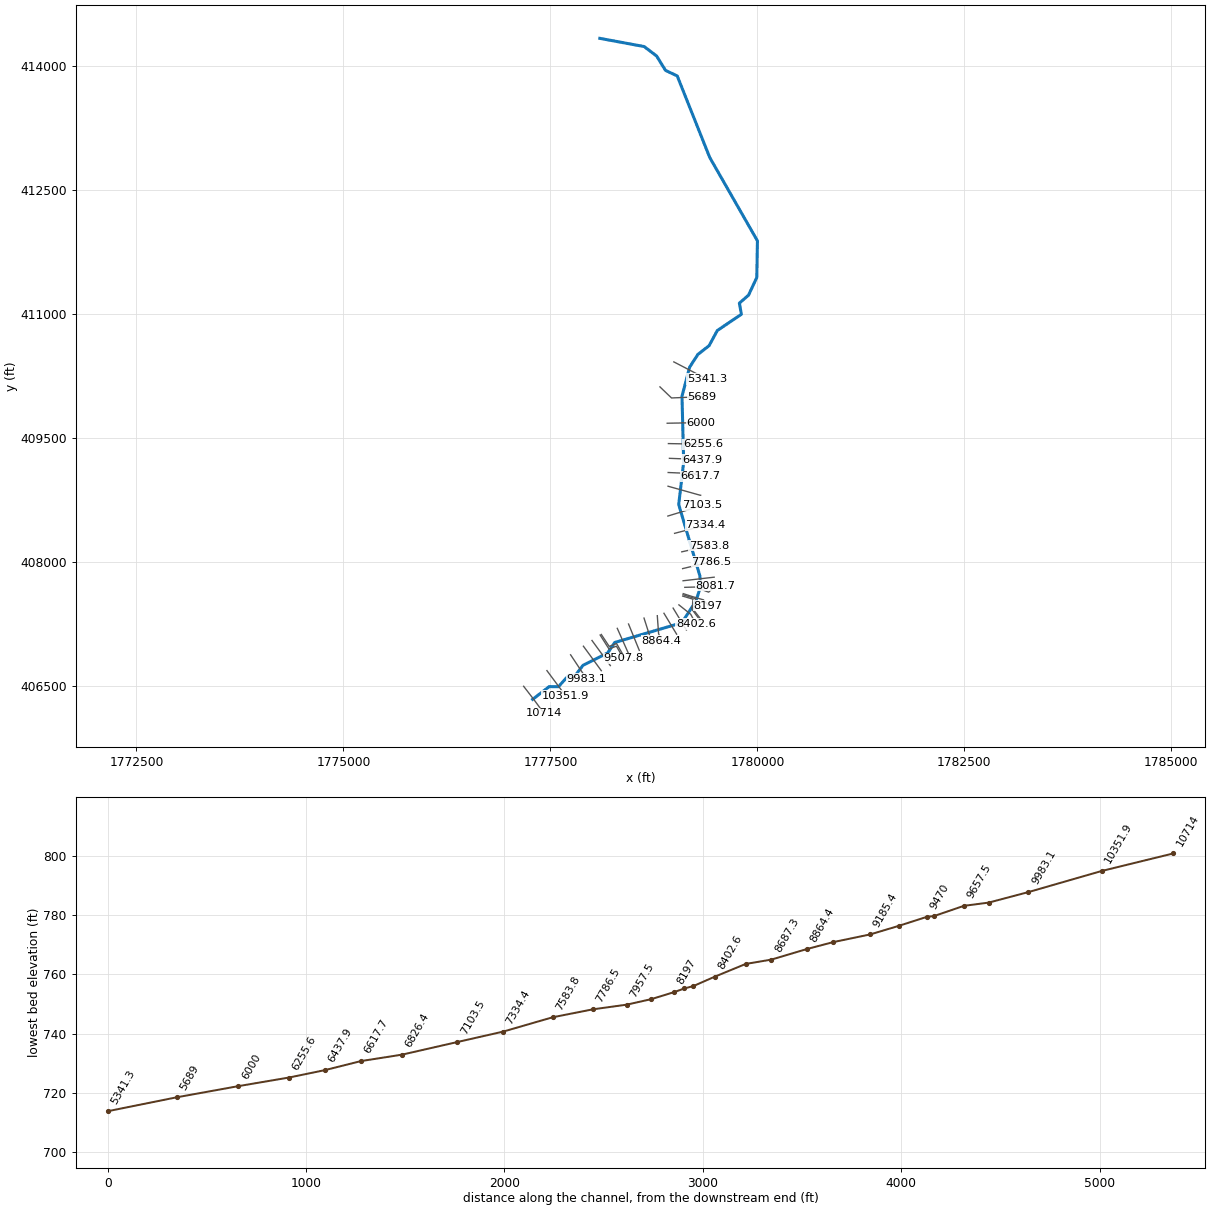
--- INDIANCK.prj (project) ---

Proj Title=INDIANCK
Current Plan=p01
Default Exp/Contr=0,0
English Units
Geom File=g01
Flow File=f01
Plan File=p01
BEGIN DESCRIPTION:
END DESCRIPTION:
DSS Export Rating Curves= 0
DSS Export Rating Curve Sorted= 0
DSS Export Volume Flow Curves= 0
DXF OffsetX= 0
DXF OffsetY= 0
DXF ScaleX= 0
DXF ScaleY= 0

--- INDIANCK.p01 (plan) ---

Plan Title=Floodplain
Program Version=4.00
Geom File=g01
Flow File=f01
K Sum by GR=0
Std Step Tol=0.01
Critical Tol=0.01
Num of Std Step Trials=20
Max Error Tol=0.3
Flow Tol Ratio=0.001
Split Flow NTrial=30
Split Flow Tol=0.02
Split Flow Ratio=0.02
Log Output Level=0
Friction Slope Method=1
Unsteady Friction Slope Method=2
Unsteady Bridges Friction Slope Method=1
Global Log Level=0
CheckData=False
Run HTab=0
Run UNet=0
Run PostProcess=0
UNET Theta=0
UNET Theta Warmup=0
UNET ZTol=0
UNET ZSATol=0
UNET MxIter=0
UNET MaxInSteps=0
UNET DtIC=0
UNET DtMin=0
UNET MaxCRTS=0
UNET WFStab=0
UNET SFStab=0
UNET WFX=0
UNET SFX=0
UNET DSS MLevel=0
UNET DZMax Abort=0
UNET Convert EG Bridges=0
UNET Use Existing IB Tables=0
UNET Froude Limit=0
UNET Froude Power=0
Write IC File=0
Echo Input=False
Echo Output=False
Write Detailed=0

--- INDIANCK.f01 (steady flow) ---

Flow Title=NFF Regression Equation
Program Version=4.10
Number of Profiles= 1
Profile Names=P100yr
River Rch & RM=INDIANCK,Main            ,10714
 894.086
River Rch & RM=INDIANCK,Main            ,8293.6
940.2164
River Rch & RM=INDIANCK,Main            ,8081.7
1161.237
River Rch & RM=INDIANCK,Main            ,6826.4
 1177.23
River Rch & RM=INDIANCK,Main            ,6437.9
1344.872
River Rch & RM=INDIANCK,Main            ,4542.4
1437.678
River Rch & RM=INDIANCK,Main            ,457.2
1592.804
River Rch & RM=INDIANCK,Main            ,289
1594.586
Boundary for River Rch & Prof#=INDIANCK,Main            , 1
Up Type= 0
Dn Type= 3
Dn Slope=0.0034
DSS Import GetInterval= 0
DSS Import GetPeak= 0
DSS Import FillOption= 0

--- INDIANCK.g01 (geometry) ---

Geom Title=USGS 10m DEM
Program Version=4.10

River Reach=INDIANCK        ,Main
Reach XY= 30
     1777285.609      406338.757     1777485.278      406492.856
     1777596.805      406491.657     1777720.324      406628.248
     1777801.271      406629.447     1777893.611      406749.967
     1778191.616       406899.57      1778276.76      407026.087
     1779088.029      407264.851     1779255.919      407523.221
     1779312.282      407695.249     1779305.087      407832.559
     1779049.654      408693.476     1779109.615       409206.44
     1779089.228      410002.839     1779181.568      410354.569
     1779280.503      410507.468     1779416.614      410613.899
     1779516.149      410797.379     1779806.959      410993.451
     1779782.375      411127.763     1779893.302      411224.899
     1779992.837      411438.359     1780000.632       411881.17
     1779424.409      412888.511     1779031.599      413874.788
     1778889.932      413941.455     1778782.293      414115.761
     1778632.293      414229.649     1778096.356      414329.042

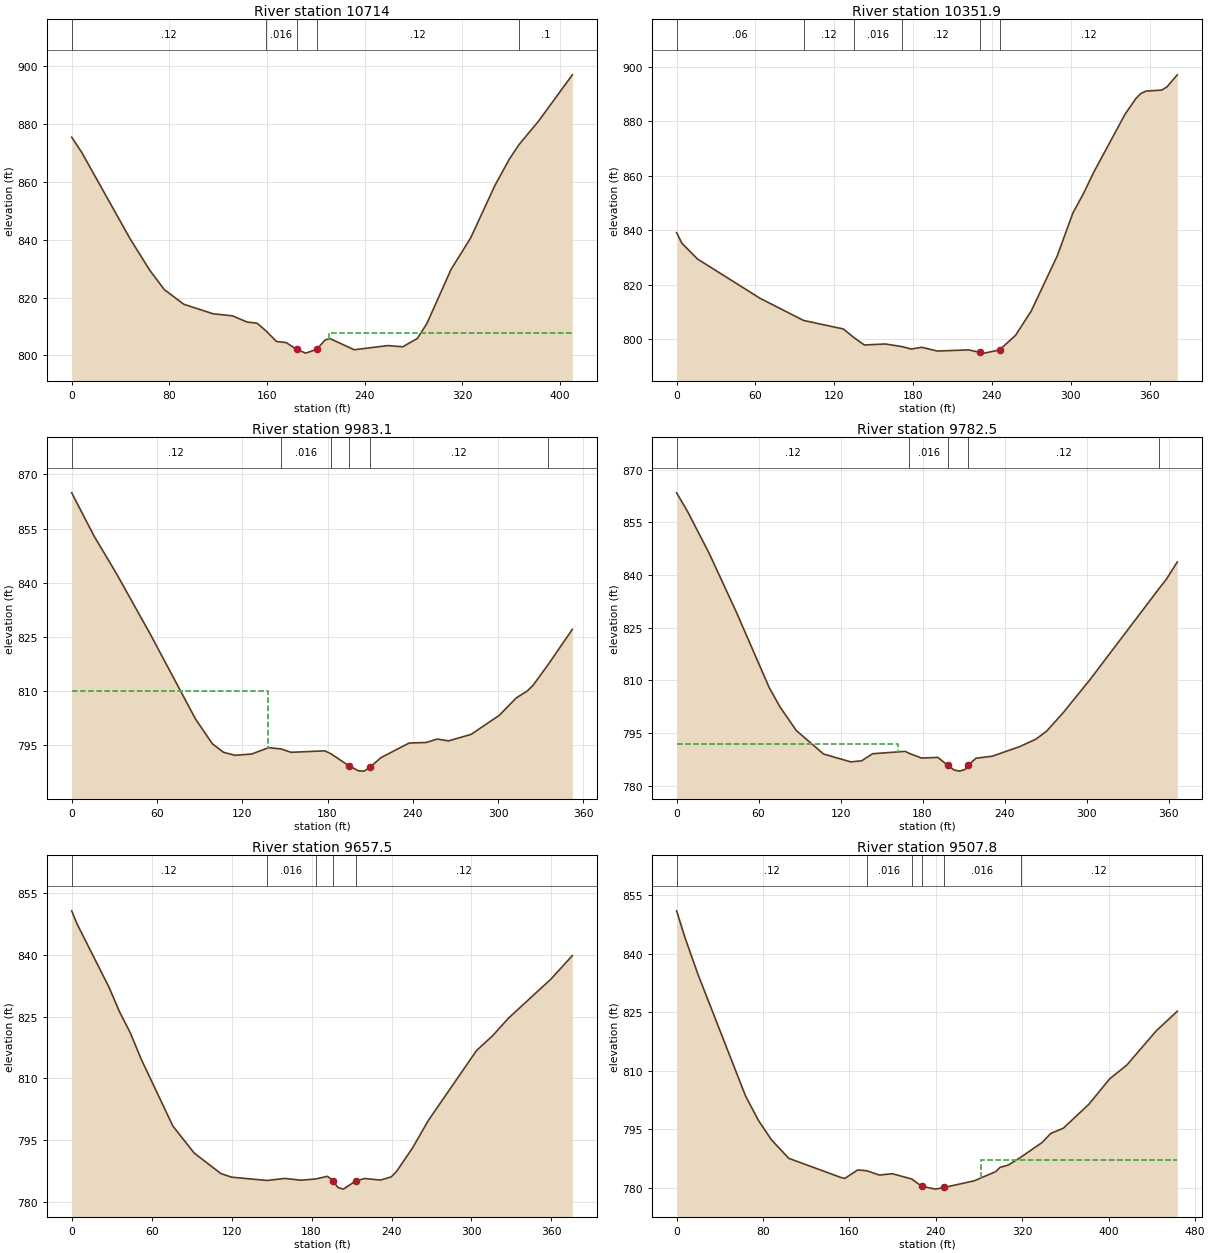
Type RM Length L Ch R = 1 ,10714   ,362.3,362.1,361.5
XS GIS Cut Line= 3
     1777176.539      406496.631     1777293.529      406344.862
     1777423.297      406169.219
#Sta/Elev= 30
       0  875.45       8  870.35    47.9  840.27    63.9  829.46    75.8  822.75
    91.8  817.67   115.8  814.38   131.7  813.66   143.7  811.51   151.7  811.14
  158.79808.6095   167.7   804.8   175.7  804.41   184.1  802.08   191.6  800.77
  200.63  802.07   207.5  805.31   211.5  805.81   231.3  801.94   259.1  803.38
     271  802.95     283  805.82   290.9  811.03   310.7  829.75   326.6  840.52
   346.5  858.69   358.4  867.87   366.3  872.89   382.2  880.94     410  897.02
#Mann= 5 ,-1 , 0
       0     .12       0  158.79    .016       0   184.1    .045       0
  200.63     .12       0   366.3      .1       0
#XS Ineff= 2 , 0
                          210.67          807.78
Permanent Ineff=
       F       F
Bank Sta=184.1,200.63
XS Rating Curve= 0 ,0
Exp/Cntr=0.3,0.1

Type RM Length L Ch R = 1 ,10351.9 ,369.9,368.8,365.9
XS GIS Cut Line= 2
     1777457.881      406685.948     1777685.086      406379.954
#Sta/Elev= 30
       0  839.13       4  835.24    15.9  829.44    63.5     815   96.61806.8583
     127  803.71  134.93 800.572   142.9  797.84   158.8   798.2  171.72797.2294
   178.6  796.33   186.6  796.99   198.5  795.61   222.3  796.02   230.8  795.14
   234.2  794.84   245.8  796.01     258  801.38     270  810.38   289.8  830.65
   301.7   846.4   309.7  853.48   317.6  861.41   341.4  882.68   349.4   888.3
   353.3  890.24   357.3  891.14   369.2  891.52   373.2  892.66   381.1  897.13
#Mann= 6 ,-1 , 0
       0     .06       0   96.61     .12       0  134.93    .016       0
  171.72     .12       0   230.8    .045       0   245.8     .12       0
Bank Sta=230.8,245.8
XS Rating Curve= 0 ,0
Exp/Cntr=0.3,0.1

Type RM Length L Ch R = 1 ,9983.1  ,199.3,200.6,201.3
XS GIS Cut Line= 2
     1777743.719      406877.357     1777938.412      406583.876
#Sta/Elev= 30
       0  864.89    15.8  852.87    31.7  842.35    55.4  825.63    87.1  802.19
    98.9  795.34   106.8  792.96   114.8  792.13   126.6  792.48   138.5  794.24
  147.04 793.912   154.3  792.96   178.1  793.36  182.48792.5224   194.9  789.25
   201.8  787.82   205.8  787.74   209.9  788.85   217.6  791.49   237.4  795.53
   249.3  795.68   257.2  796.63   265.1  796.13     281  797.93   300.8  803.21
   312.6  807.99   320.5  809.97   324.5  811.49  335.12 817.244   352.2  827.05
#Mann= 6 ,-1 , 0
       0     .12       0  147.04    .016       0  182.48     .12       0
   194.9    .045       0   209.9     .12       0  335.12      .1       0
#XS Ineff= 2 , 0
           138.2  809.85
Permanent Ineff=
       F       F
Bank Sta=194.9,209.9
XS Rating Curve= 0 ,0
Exp/Cntr=0.3,0.1

Type RM Length L Ch R = 1 ,9782.5  ,124.9,125,125.1
XS GIS Cut Line= 2
     1777898.555      406981.042     1778114.655       406685.11
#Sta/Elev= 30
       0  863.41       8  858.12    23.9  846.13    43.8  829.39    67.7  808.04
    75.7  802.44    87.6  795.75   107.5  789.07   127.5  786.82   135.4  787.13
   143.4  789.14   167.3  789.81  170.39789.2229   179.2  787.92   191.2  788.09
   198.4  785.88   203.1   784.5   207.1  784.19   211.1  784.66   213.4  785.86
   219.1  787.86     231  788.44   250.9  791.14   262.9  793.28   270.8  795.57
   282.8  800.77   302.7  810.32  353.26836.2552   358.5  838.85   366.4  843.72
#Mann= 5 ,-1 , 0
       0     .12       0  170.39    .016       0   198.4    .045       0
   213.4     .12       0  353.26      .1       0
#XS Ineff= 2 , 0
          162.36  791.86
Permanent Ineff=
       F       F
Bank Sta=198.4,213.4
XS Rating Curve= 0 ,0
Exp/Cntr=0.3,0.1

Type RM Length L Ch R = 1 ,9657.5  ,113.1,149.7,181.1
XS GIS Cut Line= 2
     1778002.093      407050.375     1778223.672       406746.94
#Sta/Elev= 30
       0  850.67       4   847.5      28  832.11      36  826.09      44  821.04
      52  814.76    75.9  798.43    91.9  791.86   111.9  786.89   119.9  786.01
  146.53785.2006   159.9   785.7   171.9  785.27   183.1  785.56   191.9  786.21
   195.9  785.18   199.8   783.5   203.8   783.1     213  785.04   219.8  785.68
   231.8   785.3   239.8  786.08   243.8   787.4   255.8  793.12   267.8  799.86
   303.8  816.75   315.8  820.33   327.8  824.62   359.7  834.12   375.7  839.81
#Mann= 5 ,-1 , 0
       0     .12       0  146.53    .016       0   183.1     .12       0
   195.9    .045       0     213     .12       0
Bank Sta=195.9,213
XS Rating Curve= 0 ,0
Exp/Cntr=0.3,0.1

Type RM Length L Ch R = 1 ,9507.8  ,39.7,37.8,58.1
XS GIS Cut Line= 4
     1778100.494      407116.269      1778207.49      406947.687
     1778297.074      406981.714     1778380.738      406836.023
#Sta/Elev= 30
       0  851.03       8  843.96      20  834.58    63.9  803.51    75.9  797.23
    87.8  792.33   103.8  787.57   151.8  782.69   155.7  782.42   167.7  784.59
     176784.3862   187.7  783.28   199.7  783.62   217.7782.2637     227  780.39
   239.6  779.67   247.6  780.09   275.5   781.8   295.5  784.17   299.4  785.25
   307.2  785.86  318.72  787.86   338.5  791.66   346.3  793.93     358  795.29
   381.5  801.38     401  807.98   416.6  811.43     444  820.24   463.5  825.28
#Mann= 6 ,-1 , 0
       0     .12       0     176    .016       0   217.7     .12       0
     227    .045       0   247.6    .016       0  318.72     .12       0
#XS Ineff= 2 , 0
                           281.6          787.22
Permanent Ineff=
       F       F
Bank Sta=227,247.6
XS Rating Curve= 0 ,0
Exp/Cntr=0.3,0.1

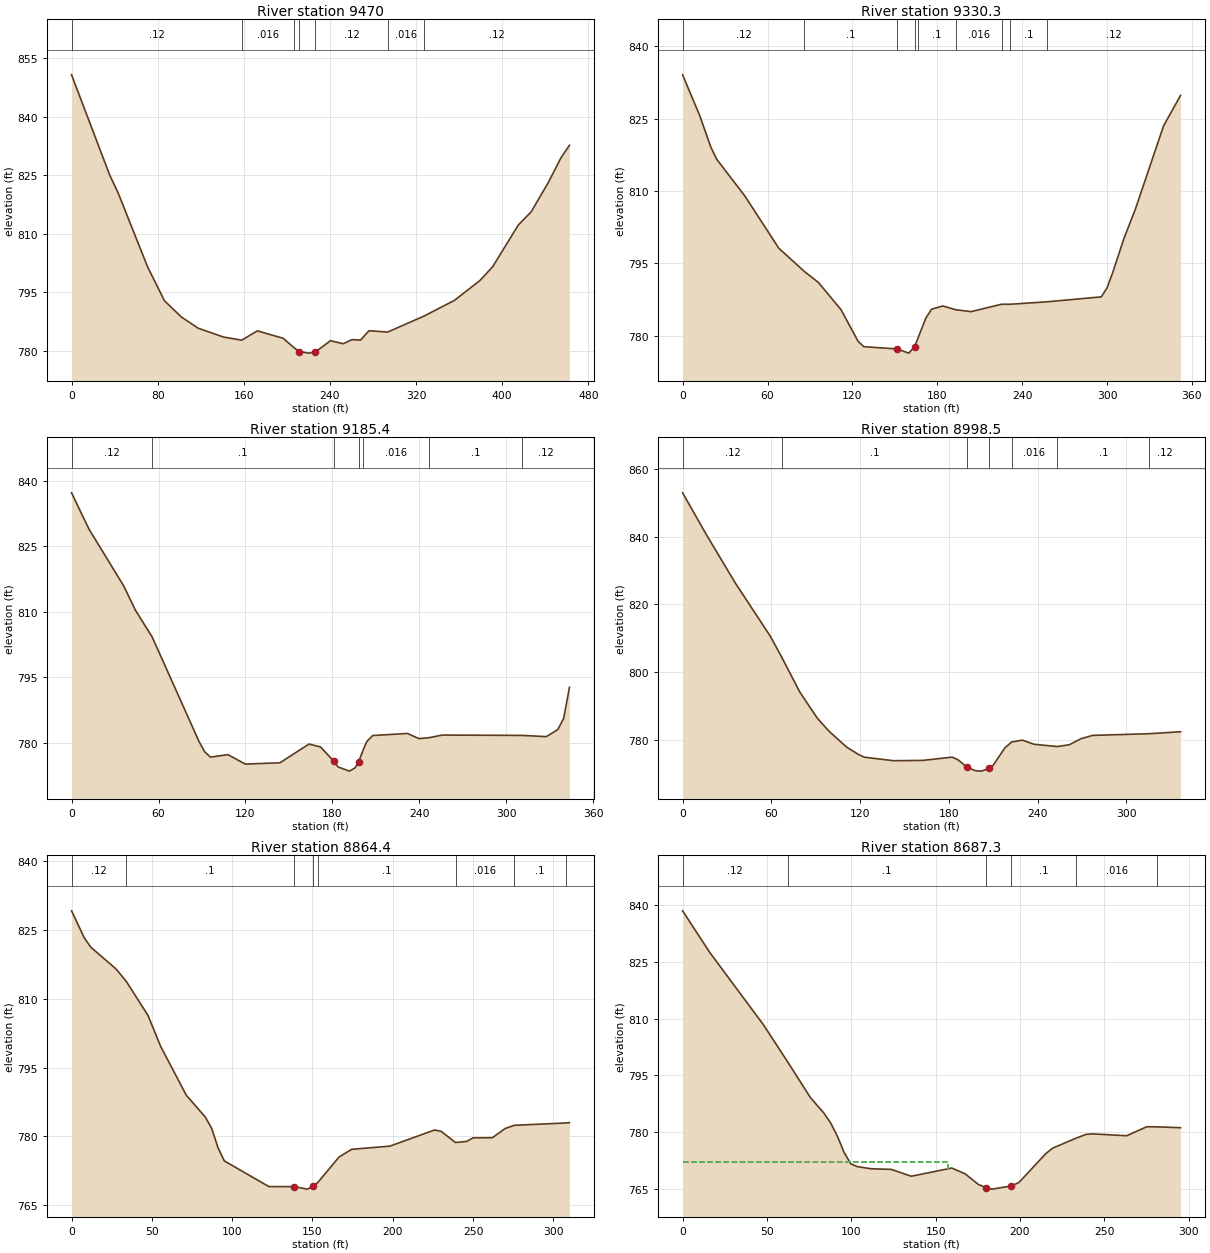
Type RM Length L Ch R = 1 ,9470    ,179.4,139.7,82.7
XS GIS Cut Line= 4
      1778114.77      407123.103     1778209.661      406978.937
     1778299.244      407012.964     1778395.945      406844.647
#Sta/Elev= 30
       0  850.75    35.3  825.13    43.2   820.5    70.6  801.52    86.3   792.8
     102  788.64   117.7  785.75   141.2  783.49  158.02782.6949   172.6  785.08
   196.6  783.17  206.88780.7057   211.5  779.78   220.5  779.37   226.5  779.66
   240.5  782.56   252.4  781.78   260.4  782.83   268.4  782.72   276.3  785.11
  293.62784.7714  327.69788.9092   355.6  792.89   379.3  797.98   391.2  801.54
     415  812.24   426.9  815.59   442.7  823.05   454.6  829.47   462.5  832.68
#Mann= 7 ,-1 , 0
       0     .12       0  158.02    .016       0  206.88     .12       0
   211.5    .045       0   226.5     .12       0  293.62    .016       0
  327.69     .12       0
Bank Sta=211.5,226.5
XS Rating Curve= 0 ,0
Exp/Cntr=0.3,0.1

Type RM Length L Ch R = 1 ,9330.3  ,145.5,144.9,143.8
XS GIS Cut Line= 2
     1778307.582      407197.111      1778450.42      406875.543
#Sta/Elev= 30
       0  834.06      12  825.68      20  819.04      24   816.6      44  808.94
      68  798.11   85.98793.3187      96  791.01     112  785.36     124  778.84
     128  777.71   151.4  777.24   159.9  776.37   163.9   777.7   166.4  779.52
   171.9  783.62   175.9  785.46   183.9  786.15  193.09785.3627   203.9  784.97
  225.41786.5067  231.49786.5013  257.73787.0132   295.9  788.03   299.9  789.87
   303.9  792.99   311.9  800.13   319.9  806.13   339.9  823.46   351.9  829.79
#Mann= 9 ,-1 , 0
       0     .12       0   85.98      .1       0   151.4    .045       0
   163.9    .045       0   166.4      .1       0  193.09    .016       0
  225.41     .12       0  231.49      .1       0  257.73     .12       0
Bank Sta=151.4,163.9
XS Rating Curve= 0 ,0
Exp/Cntr=0.3,0.1

Type RM Length L Ch R = 1 ,9185.4  ,188.7,186.9,185.1
XS GIS Cut Line= 2
     1778443.755      407249.379     1778573.354      406931.123
#Sta/Elev= 30
       0  837.22      12  828.92      36  815.89      44  810.37   55.63   804.2
    87.9   780.3    91.9  777.88    95.9  776.68   107.9  777.25   119.9  775.08
   143.8  775.38   163.8  779.67   171.8  779.02   181.1   775.7   183.8  774.44
   191.8  773.47   195.8  774.26   198.1  775.62  201.37778.4314   203.8  780.26
   207.8  781.62   231.8   782.1   239.7  780.92  246.97781.1389   255.7  781.73
  310.75781.6537   327.6  781.37   335.6     783   339.6  785.56   343.6  792.66
#Mann= 7 ,-1 , 0
       0     .12       0   55.63      .1       0   181.1    .045       0
   198.1      .1       0  201.37    .016       0  246.97      .1       0
  310.75     .12       0
Bank Sta=181.1,198.1
XS Rating Curve= 0 ,0
Exp/Cntr=0.3,0.1

Type RM Length L Ch R = 1 ,8998.5  ,139.6,134.1,128.5
XS GIS Cut Line= 2
     1778630.572      407321.043       1778733.1      407000.438
#Sta/Elev= 30
       0  852.87    15.8  840.74    35.6  826.32    59.4  810.55   67.32804.1827
    79.2  794.19    91.1  786.44      99  782.62   110.9  777.94   118.8  775.81
   122.8  774.98   142.6  773.94   162.4  774.03   182.2  774.99   186.1  774.24
   192.4  771.99     198  770.99     202  770.87   207.4  771.73   209.9  772.57
   217.8  777.69  222.36779.4361   229.7     780   237.6  778.78  253.37778.1113
   261.4  778.64   269.3  780.42   277.2   781.4  315.39781.8895   336.6  782.48
#Mann= 7 ,-1 , 0
       0     .12       0   67.32      .1       0   192.4    .045       0
   207.4      .1       0  222.36    .016       0  253.37      .1       0
  315.39     .12       0
Bank Sta=192.4,207.4
XS Rating Curve= 0 ,0
Exp/Cntr=0.3,0.1

Type RM Length L Ch R = 1 ,8864.4  ,166,177,188.2
XS GIS Cut Line= 3
     1778791.038      407350.029     1778806.663      407132.581
     1778843.366      407048.283
#Sta/Elev= 30
       0  829.21     7.9  823.34    11.9  821.31    27.8  816.49   34.12813.7973
    47.6  806.39    55.5  799.63    71.4  789.01    83.2  784.26    87.2  781.81
    91.2  777.54    95.1  774.66   122.9  769.06   138.5  769.06   146.7  768.51
   150.6  769.15   153.5  770.03   166.5   775.5   174.4  777.19   198.2  777.89
     226   781.4     230  781.14  239.05778.6859     246  778.91     250   779.7
     262  779.72     270  781.74  275.67782.4268  307.88782.9411     310  783.01
#Mann= 8 ,-1 , 0
       0     .12       0   34.12      .1       0   138.5    .045       0
   150.6    .045       0   153.5      .1       0  239.05    .016       0
  275.67      .1       0  307.88     .12       0
Bank Sta=138.5,150.6
XS Rating Curve= 0 ,0
Exp/Cntr=0.3,0.1

Type RM Length L Ch R = 1 ,8687.3  ,130,129.7,129.2
XS GIS Cut Line= 2
     1778871.424      407379.314     1779024.261      407126.775
#Sta/Elev= 30
       0  838.43      16  827.51    47.9  808.37   62.28798.5748    75.8  789.13
    83.8  785.04    87.8  782.43    91.8  778.92    95.7  774.73    99.7  771.66
   103.7  770.92   111.7  770.37   123.7   770.2   135.6  768.39   159.6  770.56
   167.5  769.02   175.5  766.18   179.9   765.4   183.5  764.99   194.9  765.82
   199.4  766.74   215.4  774.39   219.4   775.8  233.41778.4669   239.3  779.45
   243.3  779.56   263.3  779.08   275.2  781.45  281.15781.4271   295.2   781.2
#Mann= 6 ,-1 , 0
       0     .12       0   62.28      .1       0   179.9    .045       0
   194.9      .1       0  233.41    .016       0  281.15     .12       0
#XS Ineff= 2 , 0
          157.58  772.14
Permanent Ineff=
       F       F
Bank Sta=179.9,194.9
XS Rating Curve= 0 ,0
Exp/Cntr=0.3,0.1

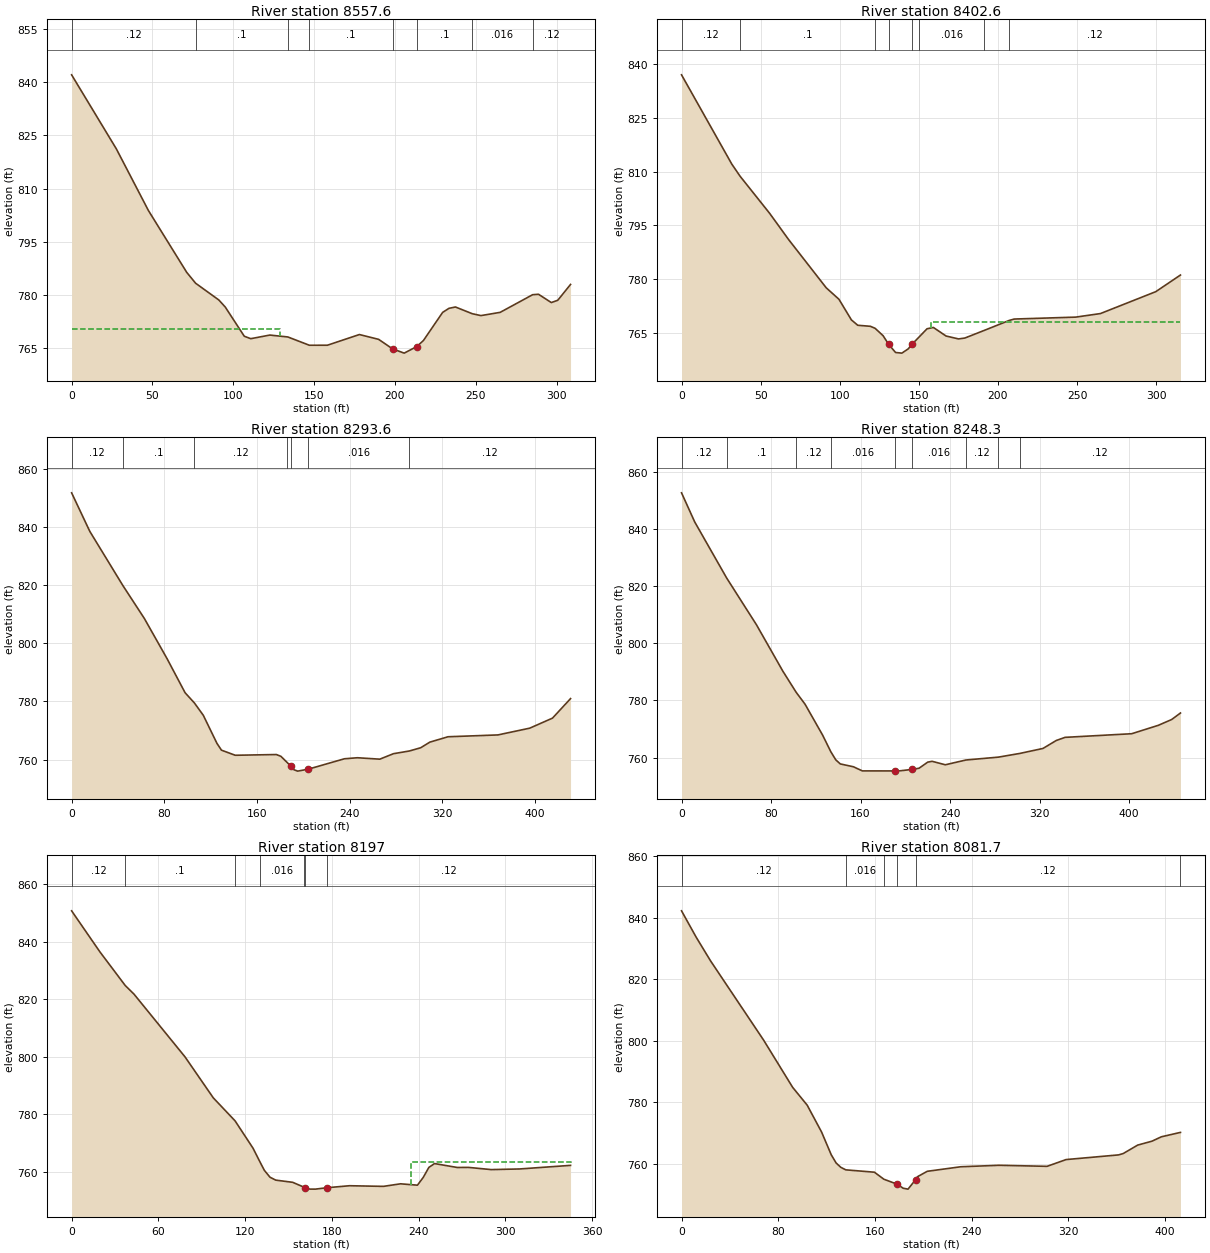
Type RM Length L Ch R = 1 ,8557.6  ,147.1,155.1,162.7
XS GIS Cut Line= 2
     1778982.101      407441.814     1779141.877       407177.81
#Sta/Elev= 30
       0  842.12    27.7  821.18    47.5   803.8    71.2  786.33    76.7783.2615
      91  778.55      95  776.56   106.8  768.29   110.8   767.6   122.6  768.62
  133.75 768.085  147.06765.7416   158.2  765.75     178  768.77   189.9  767.41
   198.5  764.73   205.7  763.52   213.5  765.37   217.6  767.08   229.5  775.03
   233.4  776.17   237.4  776.55  247.84774.6481   253.2  774.12   265.1  775.04
  285.16780.0217   288.8  780.14   296.7   777.8   300.7  778.45   308.6  782.92
#Mann= 8 ,-1 , 0
       0     .12       0    76.7      .1       0  133.75     .12       0
  147.06      .1       0   198.5    .045       0   213.5      .1       0
  247.84    .016       0  285.16     .12       0
#XS Ineff= 2 , 0
          128.79  770.33
Permanent Ineff=
       F       F
Bank Sta=198.5,213.5
XS Rating Curve= 0 ,0
Exp/Cntr=0.3,0.1

Type RM Length L Ch R = 1 ,8402.6  ,132.1,108.9,57.6
XS GIS Cut Line= 3
     1779051.914      407480.862     1779195.096      407366.788
     1779257.224      407249.997
#Sta/Elev= 30
       0  837.07    31.8  812.09   37.05 808.695    55.7  798.34    67.7     791
    91.5   777.5    99.5  774.32   107.4  768.53   111.4  767.04   119.4  766.75
  122.38766.1838   127.4  764.13     131  761.67   135.3  759.43   139.3  759.25
   143.3  760.44     146  761.87  150.34763.8345   155.2  766.06   159.2  766.43
   167.2  764.04   175.1  763.22   179.1  763.47  191.45  765.62  207.14768.3911
   210.3  768.78   249.2  769.32   264.8  770.31   299.8  776.44   315.4  781.09
#Mann= 8 ,-1 , 0
       0     .12       0   37.05      .1       0  122.38     .12       0
     131    .045       0     146     .12       0  150.34    .016       0
  191.45      .1       0  207.14     .12       0
#XS Ineff= 2 , 0
                          157.79          767.93
Permanent Ineff=
       F       F
Bank Sta=131,146
XS Rating Curve= 0 ,0
Exp/Cntr=0.3,0.1

Type RM Length L Ch R = 1 ,8293.6  ,50,45.3,58.7
XS GIS Cut Line= 6
     1779097.493      407586.899     1779221.507      407549.856
     1779217.167      407490.828     1779224.111      407479.543
     1779204.146      407435.272     1779311.044      407289.927
#Sta/Elev= 30
       0   851.7    15.7  838.46   44.32819.8014    62.8  808.53    82.4  794.72
      98  782.99  105.97779.5161   113.7  775.25   125.5   765.6   129.4  763.26
   141.3  761.51   176.8  761.76   180.7  761.15  186.22759.0015   189.4  757.71
   191.9  756.55   195.2  756.06   204.4  756.74   235.5   760.3   246.7  760.66
   266.1  760.17   277.9  762.05  291.65762.9832   301.4  764.09   309.3  766.02
     325  767.87   368.1   768.5   395.6  770.83   415.2  774.27   430.8  780.98
#Mann= 7 ,-1 , 0
       0     .12       0   44.32      .1       0  105.97     .12       0
  186.22    .016       0   189.4    .045       0   204.4    .016       0
  291.65     .12       0
Bank Sta=189.4,204.4
XS Rating Curve= 0 ,0
Exp/Cntr=0.3,0.1

Type RM Length L Ch R = 1 ,8248.3  ,14.4,51.3,97.8
XS GIS Cut Line= 6
     1779101.497      407603.533     1779255.361      407554.196
     1779248.417      407488.224     1779237.132       407458.71
     1779224.238      407425.344     1779317.988      407307.288
#Sta/Elev= 30
       0  852.58    11.8  842.39   40.39822.7585      67  806.43    90.6   790.2
  102.43782.8518   110.4  778.67   126.1  767.87  133.44 762.047   137.9   759.2
   141.9  757.78   153.7  756.78   161.6  755.34   190.8  755.33   192.8  755.26
   205.8  755.84   212.3  756.27   220.1  758.41     224  758.69   235.8  757.48
   254.2 759.148  283.27760.1564  302.25761.4376   323.1  763.19     335  765.98
   342.9  767.07   402.4  768.34   426.2  771.28   438.1   773.3     446  775.58
#Mann= 9 ,-1 , 0
       0     .12       0   40.39      .1       0  102.43     .12       0
  133.44    .016       0   190.8    .045       0   205.8    .016       0
   254.2     .12       0  283.27    .016       0  302.25     .12       0
Bank Sta=190.8,205.8
XS Rating Curve= 0 ,0
Exp/Cntr=0.3,0.1

Type RM Length L Ch R = 1 ,8197    ,116.5,115.2,113.7
XS GIS Cut Line= 4
     1779104.626       407616.53     1779212.826      407581.626
     1779348.243      407541.522     1779406.576      407472.772
#Sta/Elev= 30
       0  850.81    19.6  836.52   37.13824.8146    43.1  821.87    78.4  800.05
      98  785.77  113.06777.7739   125.5  768.25  130.11763.6636   133.3  760.58
   137.2  758.18   141.2  757.16   152.9   756.4  160.91754.6711   161.5  754.57
   164.7  754.04   168.6  754.03   176.5  754.51   192.2  755.21   215.7  754.99
   227.5  755.88   239.2   755.4   243.2   758.1   247.1  761.58     251  762.92
   266.7  761.56   274.5  761.59   290.2  760.82   309.8  761.04   345.1  762.29
#Mann= 7 ,-1 , 0
       0     .12       0   37.13      .1       0  113.06     .12       0
  130.11    .016       0  160.91     .12       0   161.5    .045       0
   176.5     .12       0
#XS Ineff= 2 , 0
                          234.48          763.57
Permanent Ineff=
       F       F
Bank Sta=161.5,176.5
XS Rating Curve= 0 ,0
Exp/Cntr=0.3,0.1

Type RM Length L Ch R = 1 ,8081.7  ,113.7,124.2,134.8
XS GIS Cut Line= 4
     1779123.286      407692.737     1779243.078       407696.21
     1779410.613      407634.578     1779494.792      407711.833
#Sta/Elev= 30
       0  842.25      12  833.74      24  825.96    67.9  800.15    91.9  784.79
   103.9     779   115.8  770.26   123.8  762.85   127.8  760.19   131.7  758.76
  135.85757.9355   159.5  757.17  167.33754.8824   178.5  753.24   183.3  751.95
   187.3  751.66   193.5  754.71   195.2  755.72   203.2  757.46   230.9  758.94
   262.6  759.42   302.3  759.08     318  761.28   361.4   762.8   365.3  763.25
   377.2  765.99     389  767.26   396.8  768.69  412.07770.0833   412.6  770.12
#Mann= 6 ,-1 , 0
       0     .12       0  135.85    .016       0  167.33     .12       0
   178.5    .045       0   193.5     .12       0  412.07      .1       0
Bank Sta=178.5,193.5
XS Rating Curve= 0 ,0
Exp/Cntr=0.3,0.1

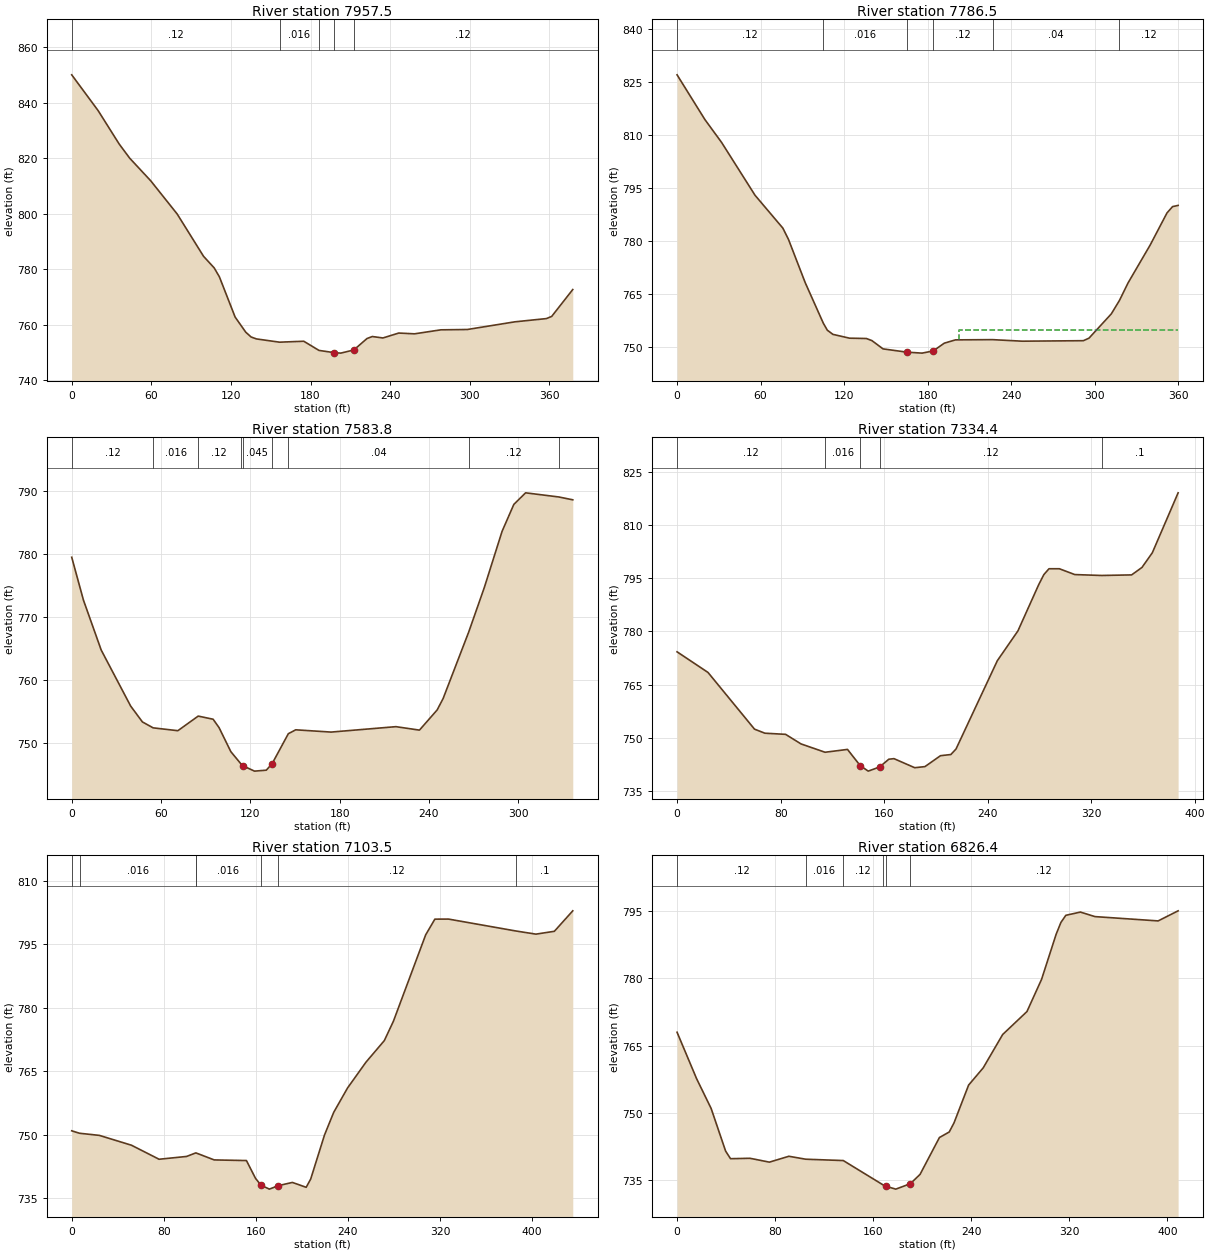
Type RM Length L Ch R = 1 ,7957.5  ,168.5,171,173.7
XS GIS Cut Line= 2
     1779102.479      407772.178     1779477.691       407815.56
#Sta/Elev= 30
       0  850.04    19.9  837.16    35.8   825.1    43.7  820.02    59.6  811.85
    79.5  799.91    99.4  784.66   107.4   780.5   111.3   777.3   123.2  762.77
   131.2  757.34   135.2  755.62   139.2  754.92  156.66 753.744   174.9  754.08
   186.4750.7775   197.6  749.99   202.8   749.8   212.6  750.93   222.6  755.06
   226.6  755.78   234.6  755.26   246.5  757.03   258.4  756.75   278.3  758.19
   298.2  758.31     334  761.07   357.8  762.24   361.8  763.02   377.7  772.71
#Mann= 5 ,-1 , 0
       0     .12       0  156.66    .016       0   186.4     .12       0
   197.6    .045       0   212.6     .12       0
Bank Sta=197.6,212.6
XS Rating Curve= 0 ,0
Exp/Cntr=0.3,0.1

Type RM Length L Ch R = 1 ,7786.5  ,202.8,202.7,202.2
XS GIS Cut Line= 2
     1779096.951      407919.068     1779446.742      408003.291
#Sta/Elev= 30
       0     827      20  814.33      32  807.85      56   792.9      76  783.59
      80  780.42      92  768.19     105 756.711   107.9  754.71   111.9  753.53
   123.9  752.45   135.9  752.36   139.9  751.77   147.9  749.42   164.9   748.5
   175.9  748.22   183.9  748.83   191.9  751.04   199.9  751.97  226.52752.0376
   247.8   751.6   291.8  751.74   295.8  752.46   311.8  759.32  317.66763.1281
   323.8  768.06   339.8  778.87   351.8   787.9   355.8  789.69   359.8  790.04
#Mann= 6 ,-1 , 0
       0     .12       0     105    .016       0   164.9    .045       0
   183.9     .12       0  226.52     .04       0  317.66     .12       0
#XS Ineff= 2 , 0
                          202.25          754.67
Permanent Ineff=
       F       F
Bank Sta=164.9,183.9
XS Rating Curve= 0 ,0
Exp/Cntr=0.3,0.1

Type RM Length L Ch R = 1 ,7583.8  ,248.7,249.5,249.7
XS GIS Cut Line= 2
     1779086.606      408121.961     1779414.969      408196.021
#Sta/Elev= 30
       0   779.5     7.9  772.68    19.8  764.77    39.6  755.87    47.5  753.35
    54.7752.4108    71.3  751.96   84.98754.2776      95  753.78      99  752.44
   106.9  748.63   113.4  746.77   114.8  746.41   122.8  745.54   130.7  745.69
   134.6  746.71  145.54 751.488   150.5   752.1   174.2  751.74   217.8   752.6
   233.6  752.05   245.5  755.26   249.5  757.07  266.65767.5984   277.2  774.71
   289.1  783.61     297  787.89   304.9  789.73   327.2789.0725   336.6  788.62
#Mann= 9 ,-1 , 0
       0     .12       0    54.7    .016       0   84.98     .12       0
   113.4    .045       0   114.8    .045       0   134.6     .12       0
  145.54     .04       0  266.65     .12       0   327.2      .1       0
Bank Sta=114.8,134.6
XS Rating Curve= 0 ,0
Exp/Cntr=0.3,0.1

Type RM Length L Ch R = 1 ,7334.4  ,229.8,230.9,231.7
XS GIS Cut Line= 2
      1778999.81      408345.525     1779374.312      408442.635
#Sta/Elev= 30
       0  774.28    23.9  768.47    59.8  752.52    67.8  751.38    83.8  751.06
    95.7  748.37  114.28 746.019   131.6  746.82   141.4  742.27   147.6  740.71
   156.4  741.88   163.5  744.06   167.5  744.22   183.5  741.67   191.4  741.98
   203.4  745.05   211.4  745.38   215.4  746.93   247.3  771.78   263.2  780.16
   279.2  793.13   283.2  795.99   287.2  797.65   295.2  797.65   307.1  796.01
  327.87795.7561     351  795.92     359  798.02     367  802.16   386.9  819.01
#Mann= 5 ,-1 , 0
       0     .12       0  114.28    .016       0   141.4    .045       0
   156.4     .12       0  327.87      .1       0
Bank Sta=141.4,156.4
XS Rating Curve= 0 ,0
Exp/Cntr=0.3,0.1

Type RM Length L Ch R = 1 ,7103.5  ,289.8,277.1,263.5
XS GIS Cut Line= 2
      1778918.67      408554.521     1779334.846      408682.028
#Sta/Elev= 30
       0  750.96    6.78750.3807      24  749.88    51.9  747.56    75.9  744.25
    99.8  744.91  107.61745.7286  107.89745.7489   123.8  744.09   151.8  743.94
   159.7  739.73   164.5  738.12   171.7   737.2   179.5  738.02   191.7  738.78
   203.7  737.63   207.6  739.57   219.6  749.96   227.6  755.31   239.6  761.05
   255.6  767.14   271.6  772.25   279.5  776.83   307.5  797.19   315.5   800.9
   327.4  800.91  385.91798.1016   403.3  797.36   419.3  798.03   435.3  802.86
#Mann= 7 ,-1 , 0
       0     .12       0    6.78    .016       0  107.61     .12       0
  107.89    .016       0   164.5    .045       0   179.5     .12       0
  385.91      .1       0
Bank Sta=164.5,179.5
XS Rating Curve= 0 ,0
Exp/Cntr=0.3,0.1

Type RM Length L Ch R = 1 ,6826.4  ,203.4,208.7,213.6
XS GIS Cut Line= 3
     1778920.825      408915.057      1779310.07      408805.729
     1779314.428      408805.881
#Sta/Elev= 30
       0  767.97    15.9  757.63    27.8  750.96    39.6  741.46    43.6  739.76
    59.5  739.85    75.3  738.99    91.2   740.3  104.91 739.644  135.59739.3433
   168.3  733.87   170.4   733.6   178.4  732.97   190.3  734.18   198.2  736.26
     214  744.48     222  745.72   225.9  747.75   237.8  756.18   249.7  760.02
   265.6  767.47   285.4  772.59   297.3  779.76   309.2  789.83   313.1  792.47
   317.1  794.06     329  794.78   340.9  793.77   392.4  792.81   408.7  795.06
#Mann= 6 ,-1 , 0
       0     .12       0  104.91    .016       0  135.59     .12       0
   168.3    .045       0   170.4    .045       0   190.3     .12       0
Bank Sta=170.4,190.3
XS Rating Curve= 0 ,0
Exp/Cntr=0.3,0.1

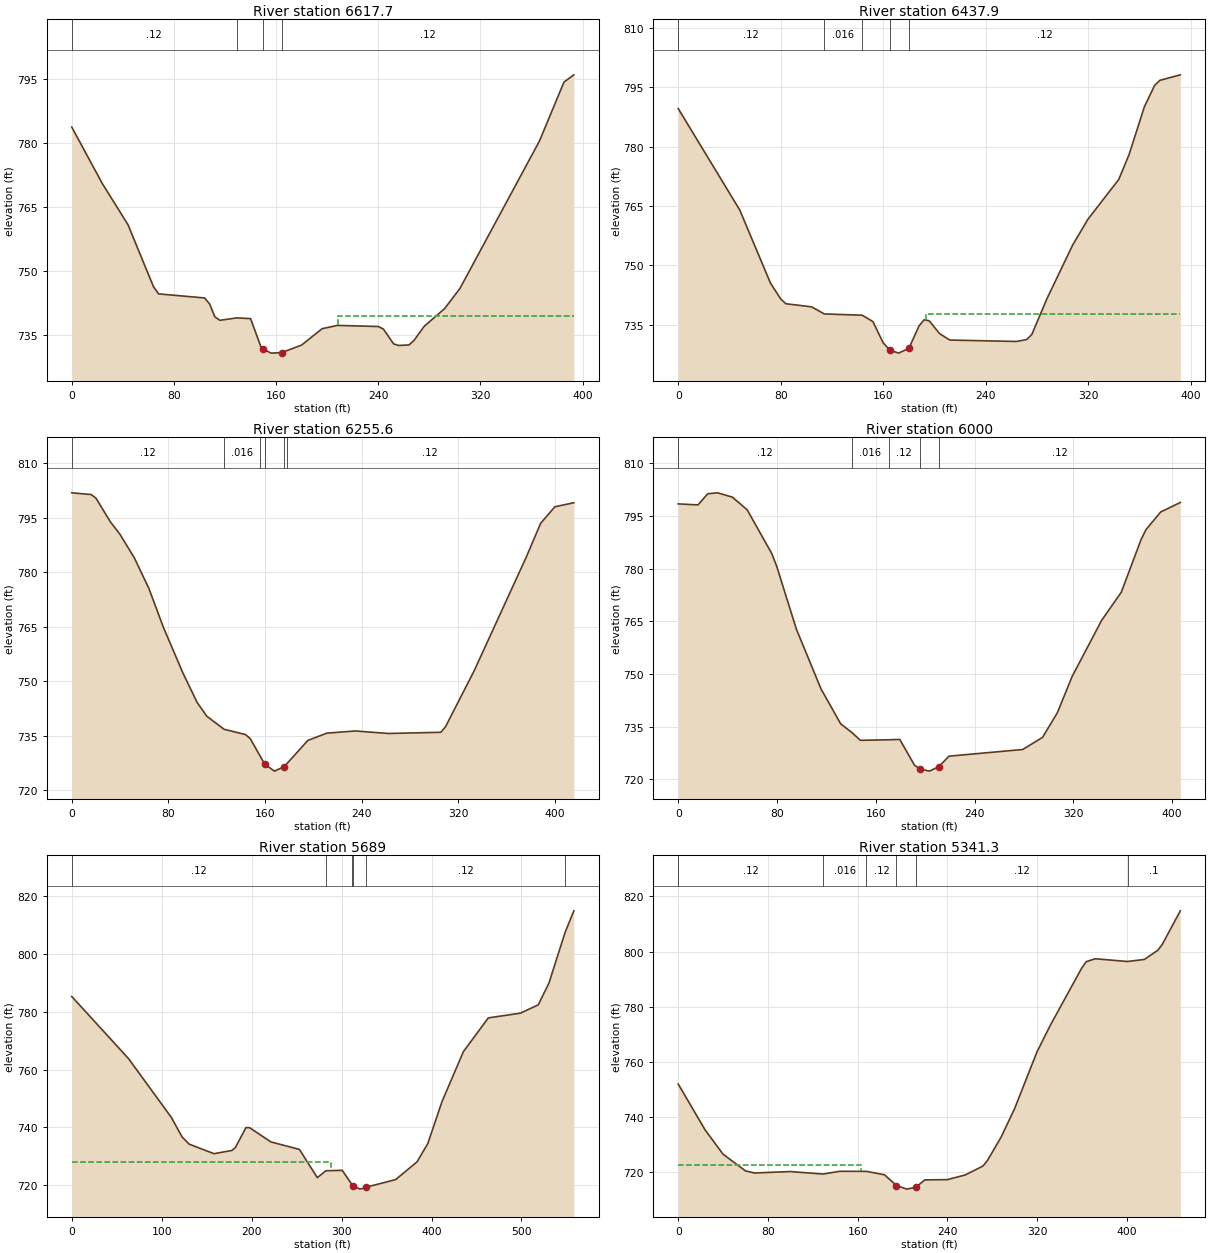
Type RM Length L Ch R = 1 ,6617.7  ,179.5,179.8,179.8
XS GIS Cut Line= 3
     1778922.257        409080.8     1779237.891      409066.997
     1779308.893      409036.734
#Sta/Elev= 30
       0  783.78      24   770.5      44  760.91      64  746.34      68  744.67
     104  743.72     108  742.28     112   739.3     116  738.48  129.24 739.041
     140  738.87     148  732.33   149.5  731.82     156  730.78   164.5  730.91
     180  732.68     196  736.51     208  737.28     240  737.02     244  736.41
     252  732.94     256  732.58     264   732.7     268  733.78   275.9  737.06
   291.9  741.21   303.9  745.94   366.1  780.47   385.4  794.35   393.1  796.04
#Mann= 4 ,-1 , 0
       0     .12       0  129.24    .016       0   149.5    .045       0
   164.5     .12       0
#XS Ineff= 2 , 0
                          208.43          739.46
Permanent Ineff=
       F       F
Bank Sta=149.5,164.5
XS Rating Curve= 0 ,0
Exp/Cntr=0.3,0.1

Type RM Length L Ch R = 1 ,6437.9  ,181.8,182.3,182.5
XS GIS Cut Line= 2
     1778937.448      409252.241     1779328.955      409237.092
#Sta/Elev= 30
       0  789.65      48  763.99      72  745.48      80  741.46      84  740.26
     104  739.48  114.01737.6815  143.57737.3574   151.9  735.75   159.9  730.39
     165  728.57   171.9  727.76     180  728.96   187.9  734.64   191.9  736.21
   195.9  735.94   203.9  732.71   211.9  731.07   263.9  730.71   271.9   731.2
   275.9  732.47   287.8  741.59   307.8  755.12   319.8  761.69   343.8  771.73
   351.8     778   363.8  790.14   371.8  795.55   375.8   796.8   391.8   798.2
#Mann= 5 ,-1 , 0
       0     .12       0  114.01    .016       0  143.57     .12       0
     165    .045       0     180     .12       0
#XS Ineff= 2 , 0
                          193.26          737.65
Permanent Ineff=
       F       F
Bank Sta=165,180
XS Rating Curve= 0 ,0
Exp/Cntr=0.3,0.1

Type RM Length L Ch R = 1 ,6255.6  ,254.6,255.6,256.4
XS GIS Cut Line= 3
     1778925.277      409430.393     1779104.996       409427.11
     1779340.994      409420.166
#Sta/Elev= 30
       0   801.9      16  801.43      20  800.45      32   793.9    39.9  790.49
    51.9  783.94    63.9  775.54    75.9  764.84    91.9  752.39   103.8  744.17
   111.8  740.39  126.12736.7822   143.8  735.33   147.8  734.22  155.66729.5928
   159.8  727.17   167.8  725.25   175.8  726.45   178.1  727.28   195.5   733.7
   211.2  735.71   234.8  736.31   262.4  735.62   305.7  735.95   309.6  737.52
   333.2  752.85   376.5  784.27   388.3   793.5   400.1  798.06   415.8  799.17
#Mann= 6 ,-1 , 0
       0     .12       0  126.12    .016       0  155.66     .12       0
   159.8    .045       0   175.8    .045       0   178.1     .12       0
Bank Sta=159.8,175.8
XS Rating Curve= 0 ,0
Exp/Cntr=0.3,0.1

Type RM Length L Ch R = 1 ,6000    ,310.2,311,311.2
XS GIS Cut Line= 2
     1778910.471      409676.539     1779317.034      409683.465
#Sta/Elev= 30
       0  798.43      16  798.14    23.9  801.32    31.9  801.58    43.8  800.36
    55.8  796.76    75.7  784.32    79.7  780.71    95.7  762.75   115.6  745.77
   131.6  735.78  140.92733.2463   147.5  731.11  170.46731.2665   179.4  731.37
   191.4  723.99   195.8  722.97   203.3  722.34   210.8  723.54   219.3   726.6
     279   728.5     295  731.95     307  738.93   318.9  749.22   342.8  765.22
   358.8  773.27   374.7  788.15   378.7  791.05   390.7  796.12   406.6  798.84
#Mann= 5 ,-1 , 0
       0     .12       0  140.92    .016       0  170.46     .12       0
   195.8    .045       0   210.8     .12       0
Bank Sta=195.8,210.8
XS Rating Curve= 0 ,0
Exp/Cntr=0.3,0.1

Type RM Length L Ch R = 1 ,5689    ,359.4,347.7,335.9
XS GIS Cut Line= 3
     1778822.928      410115.956     1778962.742      409981.888
     1779326.924      409997.385
#Sta/Elev= 30
       0  785.32    63.2  763.76   110.7  743.43   122.6  736.68   130.5  734.17
   158.1  730.86   177.9  731.97   181.8  732.95   193.7  739.91   197.7  739.86
   221.4  734.94   253.1  732.34     273  722.56  282.42724.9391   300.7   725.1
  311.98719.9435   312.3   719.8   320.5  718.58   327.3  719.25   360.1  721.89
   383.9  728.04   395.8  734.34   411.6  748.89   435.4  766.19   463.1   777.9
   498.8  779.54   518.6  782.41   530.5  789.94  548.49807.5308   558.2  814.99
#Mann= 6 ,-1 , 0
       0     .12       0  282.42    .016       0  311.98     .12       0
   312.3    .045       0   327.3     .12       0  548.49      .1       0
#XS Ineff= 2 , 0
           288.2  728.01
Permanent Ineff=
       F       F
Bank Sta=312.3,327.3
XS Rating Curve= 0 ,0
Exp/Cntr=0.3,0.1

Type RM Length L Ch R = 1 ,5341.3  ,377.3,372.5,367.2
XS GIS Cut Line= 2
     1778990.973       410417.75     1779388.527      410211.354
#Sta/Elev= 30
       0     752      24  735.34      40  726.55      60  720.51      68  719.74
     100  720.26  129.25719.3582     144  720.35   167.9 720.335     184  719.09
   194.7   715.2     204  713.89     212  714.58     220  717.24     240  717.33
     256  719.02     272   722.3     276  724.38     288  732.73     300     743
     320  763.61     332  773.35     360  794.08     364  796.37     372  797.42
  400.85796.4233   415.9  797.18   427.9  800.52   431.9   802.7   447.9   814.8
#Mann= 6 ,-1 , 0
       0     .12       0  129.25    .016       0   167.9     .12       0
   194.7    .045       0     212     .12       0  400.85      .1       0
#XS Ineff= 2 , 0
          162.92  722.65
Permanent Ineff=
       F       F
Bank Sta=194.7,212
XS Rating Curve= 0 ,0
Exp/Cntr=0.3,0.1