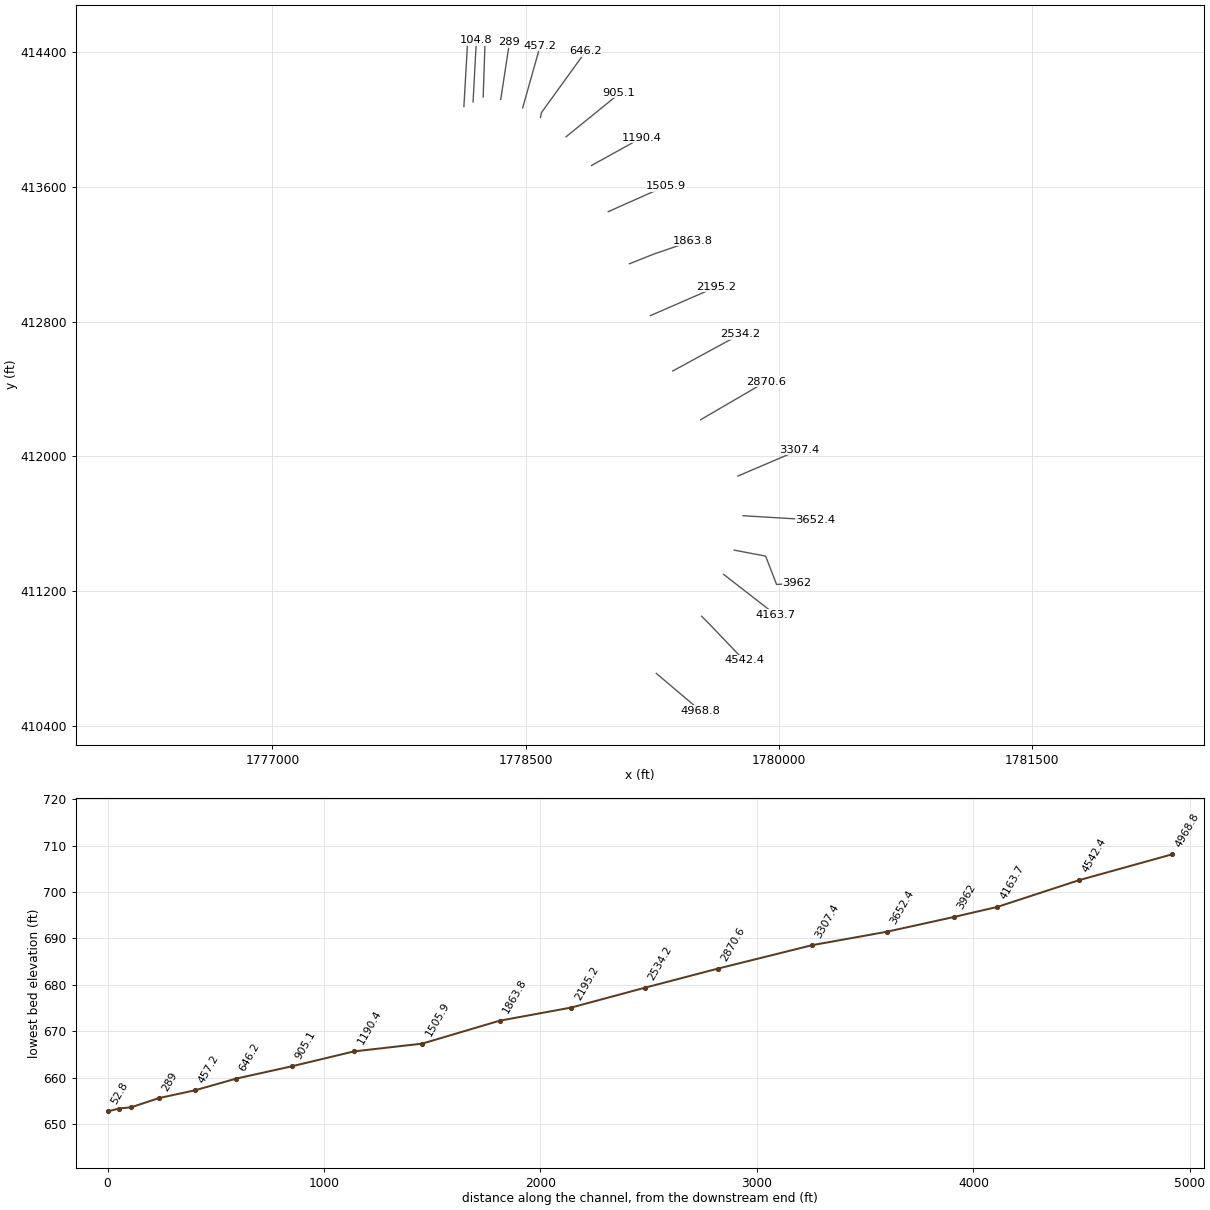
HEC-RAS study INDIANCK.prj: INDIANCK

--- INDIANCK.g01 (geometry) --- (continued)

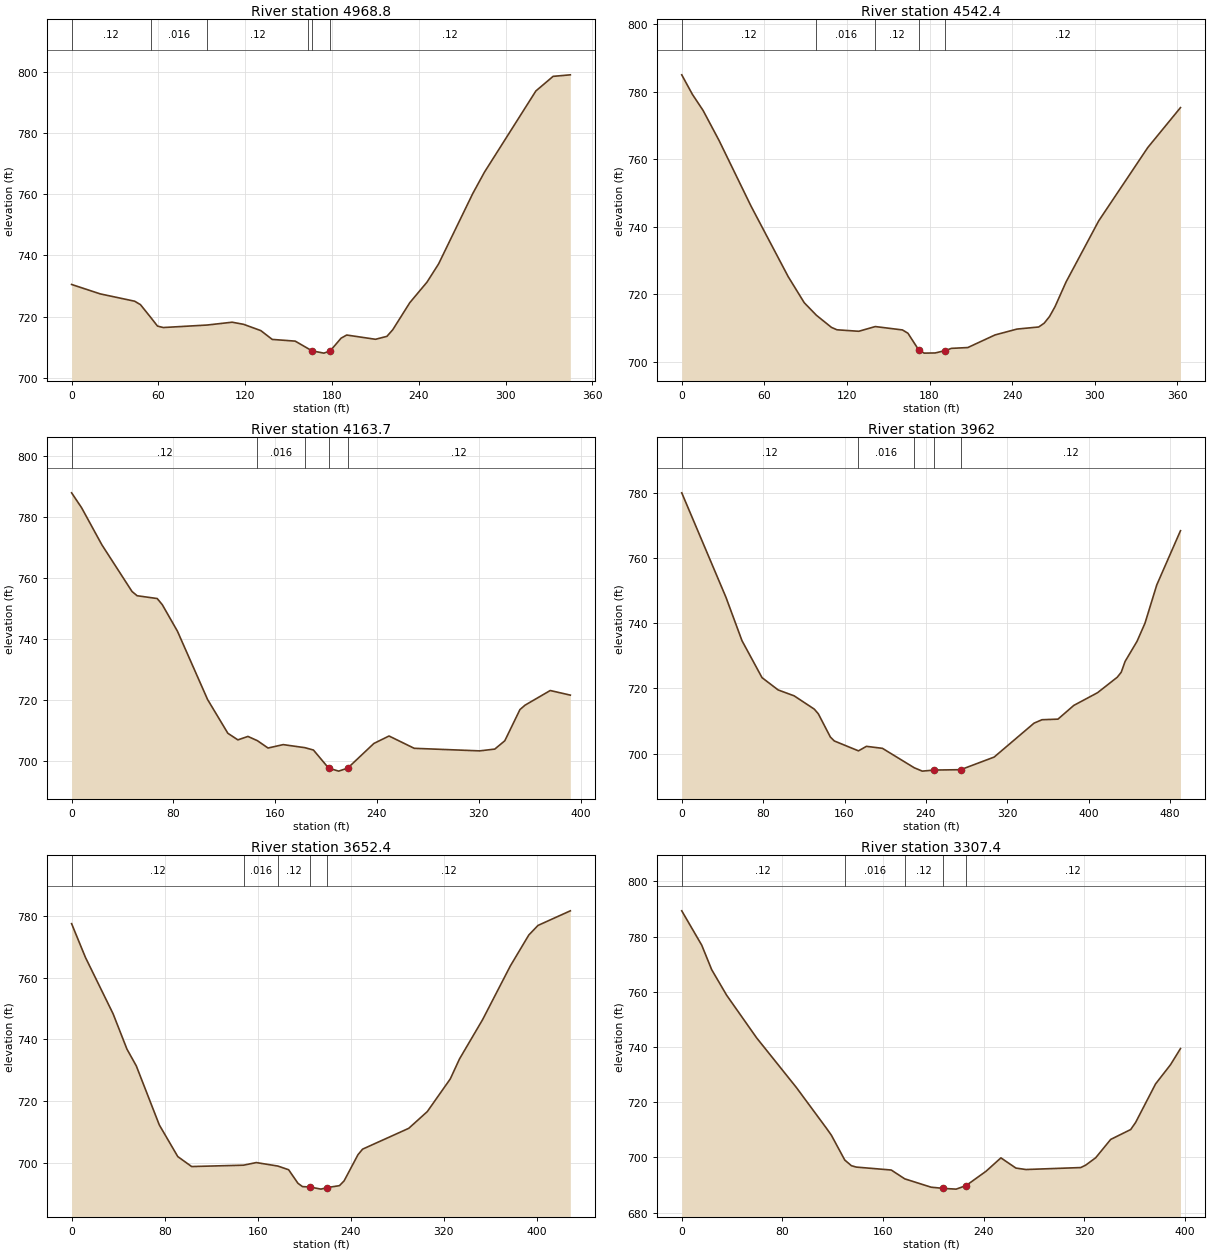
Type RM Length L Ch R = 1 ,4968.8  ,427.9,426.4,423.4
XS GIS Cut Line= 2
      1779275.37      410711.455     1779538.164      410488.215
#Sta/Elev= 30
       0  730.51    19.8  727.43    43.6  725.04    47.6  723.92   54.89719.6331
    59.4  716.91    63.4  716.44   93.65717.2531     111  718.18   118.9  717.49
   130.8  715.44   138.7  712.56   154.6     712   163.7  709.51   166.5   708.8
   174.4  708.08   178.7  708.76   186.3  712.96   190.2  713.99   210.1   712.6
     218  713.56     222   715.7   233.8  724.55   245.7  731.27   253.7   737.2
   277.4  760.26   285.4  767.17     321  793.73   332.9  798.49   344.8  798.99
#Mann= 6 ,-1 , 0
       0     .12       0   54.89    .016       0   93.65     .12       0
   163.7    .045       0   166.5    .045       0   178.7     .12       0
Bank Sta=166.5,178.7
XS Rating Curve= 0 ,0
Exp/Cntr=0.3,0.1

Type RM Length L Ch R = 1 ,4542.4  ,375.2,378.6,381.3
XS GIS Cut Line= 3
     1779544.024      411050.607     1779603.755      410990.047
     1779795.161      410789.526
#Sta/Elev= 30
       0  784.98     7.7  779.22    15.5  774.43    27.1  765.54    50.3  746.12
    77.3  725.23      89  717.48   97.83713.7684   108.8  710.17   112.8  709.47
   128.6  709.03   140.6710.4268   160.3  709.43   164.3  708.46   172.2  703.47
   176.1  702.56   184.1  702.61   191.5  703.32   195.9  703.97   207.8  704.21
   227.6  707.95   243.5  709.68   259.3   710.3   263.3  711.43   267.2  713.42
   271.2  716.35   279.1  723.57   302.9  741.73   338.5  763.42   362.3  775.27
#Mann= 5 ,-1 , 0
       0     .12       0   97.83    .016       0   140.6     .12       0
   172.2    .045       0   191.5     .12       0
Bank Sta=172.2,191.5
XS Rating Curve= 0 ,0
Exp/Cntr=0.3,0.1

Type RM Length L Ch R = 1 ,4163.7  ,217,201.7,185.8
XS GIS Cut Line= 2
     1779674.551      411299.315     1779983.905      411058.546
#Sta/Elev= 30
       0  787.89     7.9  782.98    23.8  770.87    47.5  755.58    51.5   754.2
    67.3  753.28    71.3  751.26    83.2  742.58   106.9  720.21   122.8  709.18
   130.7  707.01   138.6  708.14  146.02706.7526   154.4  704.34   166.3  705.46
  183.45704.4518   190.1  703.68     202  697.78   209.9  696.78     217  697.76
   237.6  705.84   249.5  708.28   269.3  704.25   320.7  703.41   332.6  703.99
   340.5  706.72   352.4  716.93   356.4  718.37   376.2  723.17     392  721.66
#Mann= 5 ,-1 , 0
       0     .12       0  146.02    .016       0  183.45     .12       0
     202    .045       0     217     .12       0
Bank Sta=202,217
XS Rating Curve= 0 ,0
Exp/Cntr=0.3,0.1

Type RM Length L Ch R = 1 ,3962    ,280.8,309.7,338.9
XS GIS Cut Line= 4
     1779737.329      411443.289     1779923.373      411407.853
     1779988.239      411239.584     1780108.472      411245.397
#Sta/Elev= 30
       0  779.94    43.4  747.94    59.2   734.6    78.9  723.26    94.7   719.5
   110.5  717.68   130.2  713.62   134.2  712.19     146  705.08   149.9  703.85
  173.67700.8129   181.5   702.2   197.2  701.59  228.57695.6145   236.4   694.6
   248.2  694.93   274.1  695.04     307  698.91   346.2  709.31     354  710.36
   369.7  710.54   385.3  714.76   408.6  718.65     428   723.4   431.9  724.94
   435.7  728.25   447.4   734.4   455.2  739.94   466.8   751.7   490.1  768.32
#Mann= 5 ,-1 , 0
       0     .12       0  173.67    .016       0  228.57     .12       0
   248.2    .045       0   274.1     .12       0
Bank Sta=248.2,274.1
XS Rating Curve= 0 ,0
Exp/Cntr=0.3,0.1

Type RM Length L Ch R = 1 ,3652.4  ,334.3,344.9,355.3
XS GIS Cut Line= 2
     1779789.939       411647.66        1780218.      411621.853
#Sta/Elev= 30
       0  777.58    11.9  766.63    35.7  748.31    47.6  736.85    55.6  731.44
    75.4  712.26    91.3  701.98   103.2  698.75   147.8699.1882   158.8  700.04
  177.39698.9033   186.6  697.71   194.6  693.32   198.5  692.24   204.8  692.12
   214.4  691.42   219.8  691.93   230.3  692.55   234.3   694.1   246.2  702.58
   250.2   704.4   289.9  711.16   305.8  716.58   325.6   727.2   333.5  733.67
   353.4  746.45   377.2  763.85   393.1   773.9     401  777.01   428.8  781.75
#Mann= 5 ,-1 , 0
       0     .12       0   147.8    .016       0  177.39     .12       0
   204.8    .045       0   219.8     .12       0
Bank Sta=204.8,219.8
XS Rating Curve= 0 ,0
Exp/Cntr=0.3,0.1

Type RM Length L Ch R = 1 ,3307.4  ,433.7,436.8,439.4
XS GIS Cut Line= 2
     1779759.209      411883.404     1780123.894      412039.363
#Sta/Elev= 30
       0  789.32    15.9  776.88    23.8  768.02    35.7  758.76    59.5  743.34
    91.2  725.31     115  710.62     119  708.05  129.63699.0658   134.9  697.02
   138.8  696.51   166.6  695.45  177.33692.2543   198.3  689.23   208.1  688.79
   218.2  688.53   226.1  689.81     242  695.01   253.8  699.85   265.7  696.16
   273.7  695.63   317.3  696.34   321.3  697.24   329.2   699.9   341.1  706.53
     357  710.11   360.9  712.66   376.8  726.64   388.7   733.6   396.6  739.44
#Mann= 5 ,-1 , 0
       0     .12       0  129.63    .016       0  177.33     .12       0
   208.1    .045       0   226.1     .12       0
Bank Sta=208.1,226.1
XS Rating Curve= 0 ,0
Exp/Cntr=0.3,0.1

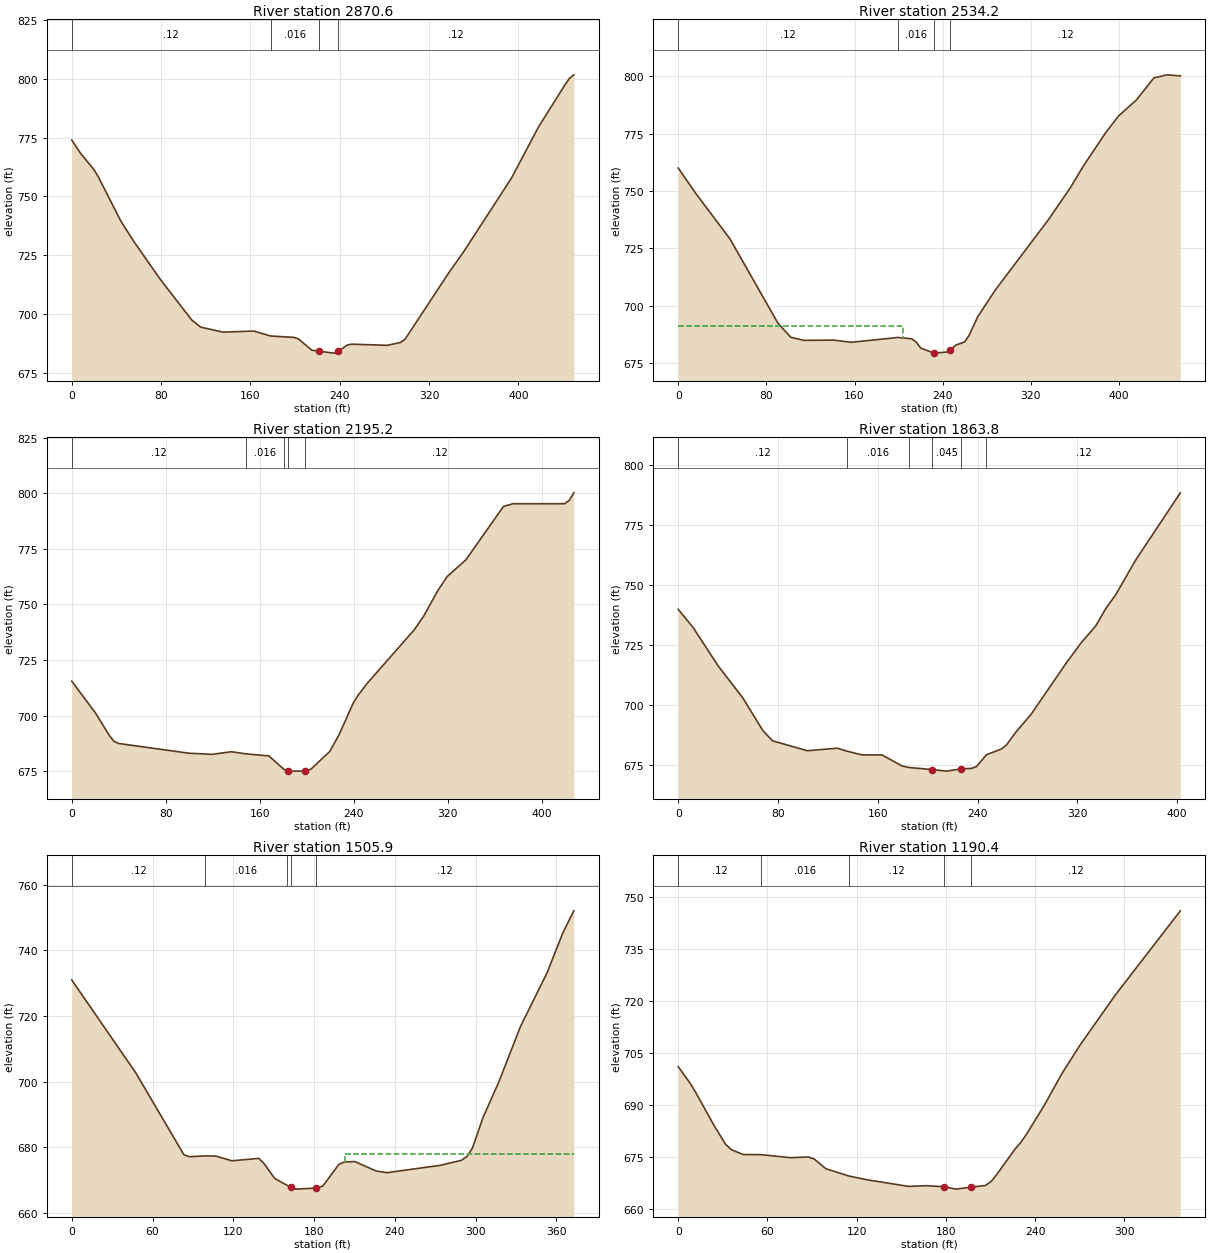
Type RM Length L Ch R = 1 ,2870.6  ,337.5,336.5,333.9
XS GIS Cut Line= 2
     1779538.002      412217.637     1779926.346      412444.653
#Sta/Elev= 30
       0  773.94       8  768.25    19.9  761.37    23.9  758.24    43.8  739.69
    55.7  730.81    79.6  714.61   107.5  697.54   115.4  694.52   135.4  692.37
   163.2  692.83  178.19 690.726     199  690.15     203  689.54     215  684.72
   221.1   684.3   234.9  683.46   238.8  684.23   246.8  686.91   250.8  687.26
   282.6  686.79   294.6     688   298.6  689.37   338.4  718.04   350.3  725.94
   394.1  757.93     418  779.39   441.9  797.47   445.8  800.14   449.8  801.66
#Mann= 4 ,-1 , 0
       0     .12       0  178.19    .016       0   221.1    .045       0
   238.8     .12       0
Bank Sta=221.1,238.8
XS Rating Curve= 0 ,0
Exp/Cntr=0.3,0.1

Type RM Length L Ch R = 1 ,2534.2  ,340.4,339,336.7
XS GIS Cut Line= 3
     1779373.084      412507.254     1779559.123      412608.928
     1779773.316      412725.068
#Sta/Elev= 30
       0  760.08    15.7  749.15    47.1  729.08    90.3  692.56   102.1  686.29
   113.9  684.92   141.3  685.02     157  684.07  199.49686.1855     212  685.59
     216  684.17     220  681.59     232  679.35   232.1  679.36     244  679.82
   247.1  680.73     252  682.87   259.9  684.22   263.9  687.01   271.9  695.28
   287.9  706.95   335.8  737.42   355.8  751.42   367.8  761.02   387.8  775.39
   399.7   782.8   415.7  789.69   431.7  799.36   443.7  800.72   455.7  800.25
#Mann= 4 ,-1 , 0
       0     .12       0  199.49    .016       0   232.1    .045       0
   247.1     .12       0
#XS Ineff= 2 , 0
          204.35  691.22
Permanent Ineff=
       F       F
Bank Sta=232.1,247.1
XS Rating Curve= 0 ,0
Exp/Cntr=0.3,0.1

Type RM Length L Ch R = 1 ,2195.2  ,333,331.5,329.4
XS GIS Cut Line= 2
     1779240.165      412835.927     1779631.839      413006.667
#Sta/Elev= 30
       0   715.5      20  701.36      32  691.11    35.9   688.5    39.9  687.52
    99.8  683.13   119.8  682.63   135.8  683.81   148.5682.8292   167.7  681.93
  180.73675.8301   183.8  675.33   187.7  675.09   198.8  675.12   203.6  675.99
   219.6  683.94   227.6  691.57   239.6  705.73   243.6  709.12   251.6  714.65
   291.5  738.62   299.5  744.78   311.5  756.17   319.4   762.5   335.4  770.03
   367.4  794.04   375.4  795.24   419.3  795.26   423.3  796.71   427.3  800.16
#Mann= 5 ,-1 , 0
       0     .12       0   148.5    .016       0  180.73     .12       0
   183.8    .045       0   198.8     .12       0
Bank Sta=183.8,198.8
XS Rating Curve= 0 ,0
Exp/Cntr=0.3,0.1

Type RM Length L Ch R = 1 ,1863.8  ,355.3,357.8,360
XS GIS Cut Line= 3
     1779115.665      413143.783      1779260.09      413201.189
     1779493.602      413281.817
#Sta/Elev= 30
       0  739.68      12  732.03    31.9  716.17    51.8  702.74    67.8  689.17
    75.7  684.85   103.6  680.75   127.5   681.8  134.99 680.602   147.4  679.02
   163.4     679   179.3  674.43  184.62673.7848   203.2  672.91   215.2  672.25
     227  673.22   235.1  673.39   239.1  674.15  247.11679.0925     259  681.46
     263  683.07     271  688.72   282.9  695.93   310.8   717.1   322.8  725.58
   334.7  732.76   342.7  739.94   350.7  745.73   366.6   760.1   402.5  788.21
#Mann= 6 ,-1 , 0
       0     .12       0  134.99    .016       0  184.62     .12       0
   203.2    .045       0     227     .08       0  247.11     .12       0
Bank Sta=203.2,227
XS Rating Curve= 0 ,0
Exp/Cntr=0.3,0.1

Type RM Length L Ch R = 1 ,1505.9  ,313.3,315.5,317.4
XS GIS Cut Line= 2
     1778990.516      413453.242     1779331.107      413605.248
#Sta/Elev= 30
       0  731.02    47.6   702.7    83.3  677.79    87.3  677.18   99.02677.4324
   107.1  677.36     119  675.94   138.9  676.67   142.8  675.12   150.8  670.54
  160.22 668.416   162.7  667.92   166.6  667.31   181.6  667.64   186.5  668.24
   198.4  674.82   202.4  675.58   210.3  675.71   226.2  672.82   234.1  672.32
   273.8  674.56   289.6   676.1   293.6  677.27   297.6  679.75   305.5  689.09
   317.4  700.08   333.3   716.8   353.1  733.21     365  745.54     373  752.08
#Mann= 5 ,-1 , 0
       0     .12       0   99.02    .016       0  160.22     .12       0
   162.7    .045       0   181.6     .12       0
#XS Ineff= 2 , 0
                          202.81          677.98
Permanent Ineff=
       F       F
Bank Sta=162.7,181.6
XS Rating Curve= 0 ,0
Exp/Cntr=0.3,0.1

Type RM Length L Ch R = 1 ,1190.4  ,280.9,285.3,289.5
XS GIS Cut Line= 2
      1778891.97      413727.787     1779187.229      413891.625
#Sta/Elev= 30
       0  700.97       8   696.2    11.9  693.44    23.8  684.22    31.8  678.61
    35.8     677    43.7  675.62   55.74675.5765    75.5   674.7    87.4  674.92
    91.4  674.33    99.3  671.52  114.78669.4156   127.1  668.32   154.9  666.42
   166.8  666.62   178.8  666.32   186.7  665.63   197.1  666.21   206.6  666.67
   210.6  667.89   214.5  670.01   226.4  677.11   230.4  679.11   234.4  681.56
   246.3   689.9   258.2  699.08   270.1   707.1     294  721.66   337.7  745.96
#Mann= 5 ,-1 , 0
       0     .12       0   55.74    .016       0  114.78     .12       0
   178.8    .045       0   197.1     .12       0
Bank Sta=178.8,197.1
XS Rating Curve= 0 ,0
Exp/Cntr=0.3,0.1

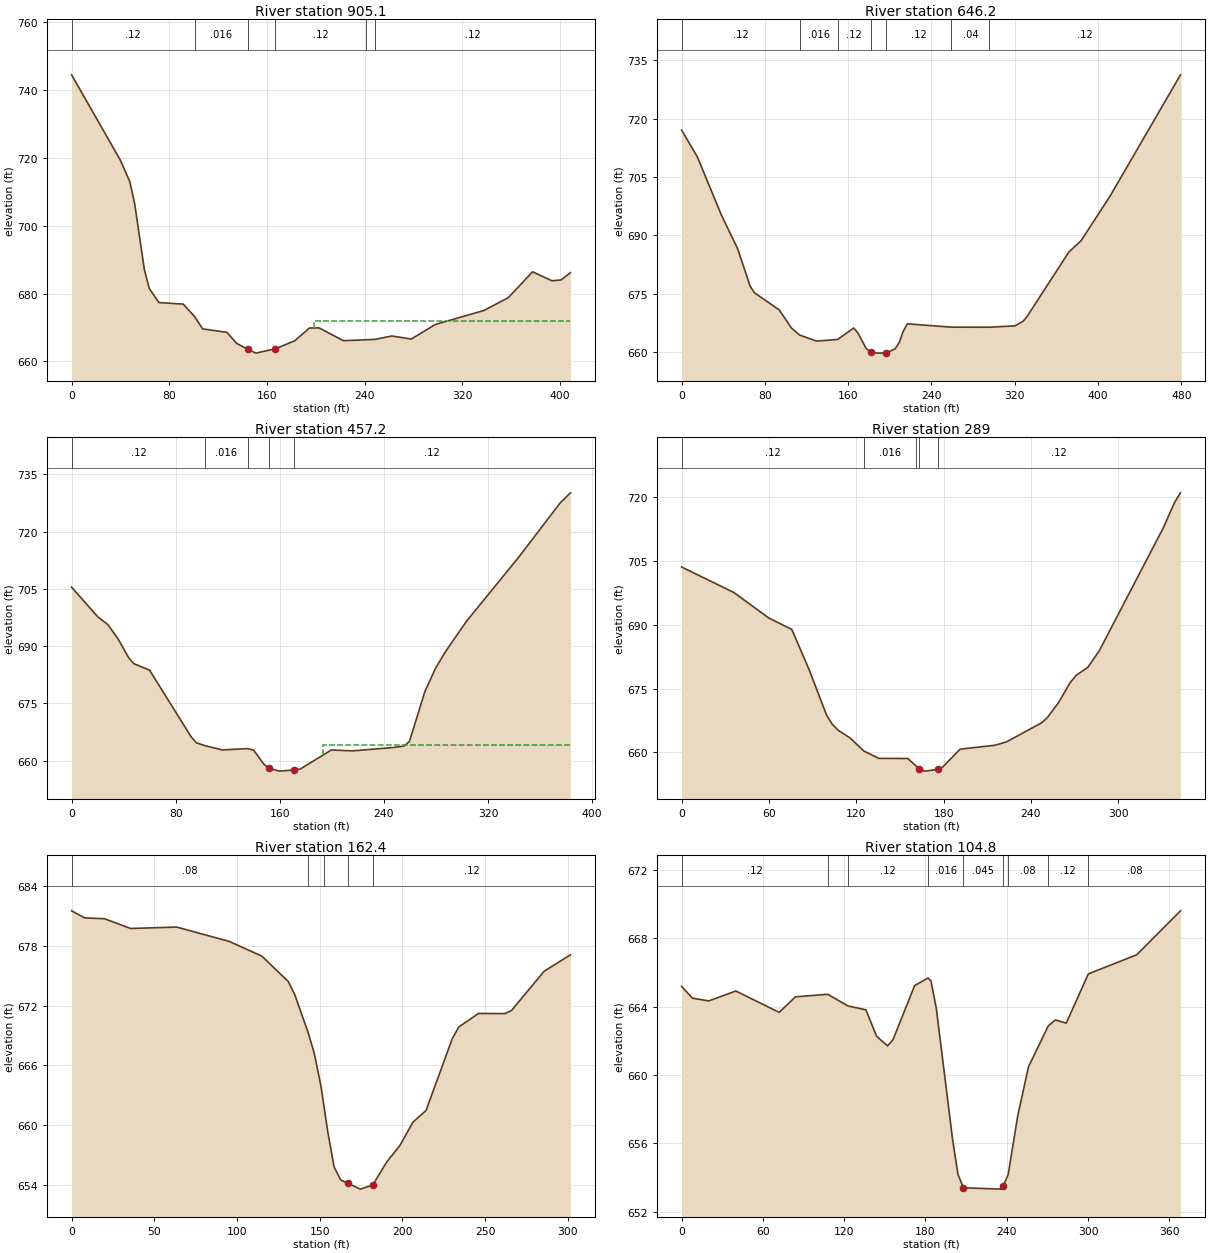
Type RM Length L Ch R = 1 ,905.1   ,252.8,259,265.1
XS GIS Cut Line= 3
     1778740.363      413898.085     1779045.856       414146.09
     1779052.067      414159.869
#Sta/Elev= 30
       0   744.5    39.8  719.42    47.7  712.96    51.7  706.42    59.6  687.05
    63.6  681.53    71.5  677.34    91.4   676.9  100.75673.2181   107.3  669.59
   127.2  668.57   135.1  665.34   144.5  663.51     151  662.44   166.9  663.73
   182.8  666.09   194.8  669.84   202.7  669.88   222.6  666.11  241.33666.3774
  248.47666.4994   262.3  667.49   278.2   666.6   298.1  670.91   337.8  675.02
   357.7   678.8   377.6  686.42   393.5  683.77     401  684.03   408.6  686.19
#Mann= 6 ,-1 , 0
       0     .12       0  100.75    .016       0   144.5    .045       0
   166.9     .12       0  241.33     .04       0  248.47     .12       0
#XS Ineff= 2 , 0
                          198.74          671.99
Permanent Ineff=
       F       F
Bank Sta=144.5,166.9
XS Rating Curve= 0 ,0
Exp/Cntr=0.3,0.1

Type RM Length L Ch R = 1 ,646.2   ,181.2,188.9,196.3
XS GIS Cut Line= 3
     1778588.755      414012.165     1778594.597       414041.75
     1778857.334      414405.847
#Sta/Elev= 30
       0  717.05    15.1  710.18    38.1   695.3      54  686.45    65.9  676.89
    69.9  675.28    93.7  670.88   105.6  666.18  113.41664.4013   129.5  662.86
  149.84663.2651   165.2  666.21   169.2     665   177.2  660.99   181.6  659.98
   189.1  659.76   196.6  659.81     205  660.85     209  662.46   212.9  665.38
   216.9  667.29   259.1666.4287  295.53666.4156   320.2  666.76   328.2  667.98
   332.1  669.27   371.9   685.7   383.8  688.66   411.6  700.11   479.2  731.25
#Mann= 7 ,-1 , 0
       0     .12       0  113.41    .016       0  149.84     .12       0
   181.6    .045       0   196.6     .12       0   259.1     .04       0
  295.53     .12       0
Bank Sta=181.6,196.6
XS Rating Curve= 0 ,0
Exp/Cntr=0.3,0.1

Type RM Length L Ch R = 1 ,457.2   ,165.6,168.2,169.6
XS GIS Cut Line= 2
     1778483.143      414069.497        1778587.      414438.497
#Sta/Elev= 30
       0  705.45      20  697.73      28  695.61    35.9  691.79    43.9  686.94
    47.9   685.4    59.9  683.72    91.8  666.27    95.8   664.7  102.68663.9128
   115.8  662.82  135.18663.1569   139.8  662.77   147.7  659.11   151.7     658
   159.7  657.26   170.9  657.58   175.7  657.81   199.6  662.81   215.6  662.56
   247.6  663.46   255.6  663.85   259.6  665.06   271.5  678.14   279.5  684.12
   287.5  688.68   303.5  696.56   343.4  713.25   375.4  727.52   383.3  730.17
#Mann= 5 ,-1 , 0
       0     .12       0  102.68    .016       0  135.18     .12       0
   151.7    .045       0   170.9     .12       0
#XS Ineff= 2 , 0
                          193.26          664.23
Permanent Ineff=
       F       F
Bank Sta=151.7,170.9
XS Rating Curve= 0 ,0
Exp/Cntr=0.3,0.1

Type RM Length L Ch R = 1 ,289     ,123.7,126.6,130.2
XS GIS Cut Line= 2
     1778353.136      414120.079     1778404.989       414458.85
#Sta/Elev= 30
       0   703.6    35.9   697.6    59.8  691.62    75.7   688.9    87.7  679.35
    99.6  668.73   103.6  666.55   107.6  665.16   115.6   663.4  125.25660.2806
   135.5  658.56   155.4  658.54   161.2  656.72   163.4  655.96   167.4  655.56
   176.2  655.98   179.3   656.5   191.3  660.73   215.2  661.65   223.2  662.45
   247.1  666.89   251.1   668.1     259  671.73     267  676.42     271  678.09
     279  679.98   286.9  683.87   330.8  712.75   338.7  718.83   342.7  721.06
#Mann= 5 ,-1 , 0
       0     .12       0  125.25    .016       0   161.2    .045       0
   163.4    .045       0   176.2     .12       0
Bank Sta=163.4,176.2
XS Rating Curve= 0 ,0
Exp/Cntr=0.3,0.1

Type RM Length L Ch R = 1 ,162.4   ,58.4,57.6,56.3
XS GIS Cut Line= 2
     1778249.099      414134.215     1778259.311       414435.63
#Sta/Elev= 30
       0  681.51     7.9   680.8    19.8  680.72    35.7  679.74    63.5  679.88
    95.2  678.45   115.1  676.96     131  674.42   134.9  673.11  143.07669.2736
   146.8  667.16   150.8   663.9  152.35662.1679   154.8  659.43   158.7  655.83
   162.7  654.52   167.1  654.18   174.6   653.6   182.1  654.02   190.5  656.32
   198.4  657.95   206.4  660.32   214.3  661.49   230.2  668.71   234.1  669.86
     246  671.22   261.9   671.2   265.9   671.5   285.7  675.45   301.6   677.1
#Mann= 5 ,-1 , 0
       0     .08       0  143.07     .12       0  152.35    .016       0
   167.1    .045       0   182.1     .12       0
Bank Sta=167.1,182.1
XS Rating Curve= 0 ,0
Exp/Cntr=0.3,0.1

Type RM Length L Ch R = 1 ,104.8   ,52,52,51.9
XS GIS Cut Line= 3
     1778189.124      414104.866     1778207.227      414444.311
     1778208.312      414472.523
#Sta/Elev= 30
       0  665.19       8   664.5      20  664.34      40  664.92      72  663.67
      84  664.58  107.92664.7284  122.72664.0464     136  663.82     144  662.26
     152  661.71     156  662.07     172  665.24  181.88 665.679     184  665.52
     188   663.9     200  656.23     204  654.19     208  653.41     236  653.33
  237.25  653.51  241.03654.1806     248  657.58     256  660.48  270.61662.8791
   275.9  663.23   283.9  663.04  300.19665.9203   335.9  667.04   368.2  669.61
#Mann= 9 ,-1 , 0
       0     .12       0  107.92     .08       0  122.72     .12       0
  181.88    .016       0     208    .045       0  237.25    .016       0
  241.03     .08       0  270.61     .12       0  300.19     .08       0
Bank Sta=208,237.25
XS Rating Curve= 0 ,0
Exp/Cntr=0.3,0.1

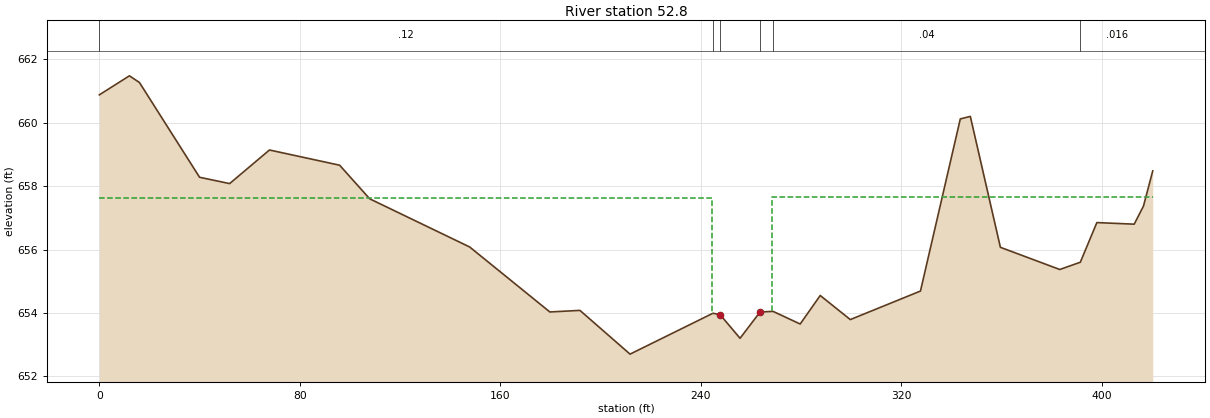
Type RM Length L Ch R = 1 ,52.8    ,51.6,52.8,54.1
XS GIS Cut Line= 3
     1778134.783      414077.101     1778156.475      414456.093
     1778186.866      414483.241
#Sta/Elev= 30
       0  660.88      12  661.48      16  661.27      40  658.28      52  658.08
    67.9  659.14    95.9  658.66   107.9   657.6   147.8  656.08   179.8  654.03
   191.8  654.08   211.8   652.7   244.9  653.99   247.8  653.94   255.7   653.2
   263.7  654.03  268.89654.0478   279.7  653.65   287.7  654.55   299.7  653.79
   327.7  654.69   343.6  660.12   347.6   660.2   359.6  656.07   383.3  655.37
   391.5655.5994   398.1  656.85     413   656.8   416.7  657.37   420.4  658.48
#Mann= 6 ,-1 , 0
       0     .12       0   244.9    .045       0   247.8    .045       0
   263.7     .12       0  268.89     .04       0   391.5    .016       0
#XS Ineff= 2 , 0
          244.38  657.62  268.26          657.65
Permanent Ineff=
       F       F
Bank Sta=247.8,263.7
XS Rating Curve= 0 ,0
Exp/Cntr=0.3,0.1

Chan Stop Cuts=-1
Use User Specified Reach Order=0
Composite Channel Slope=5